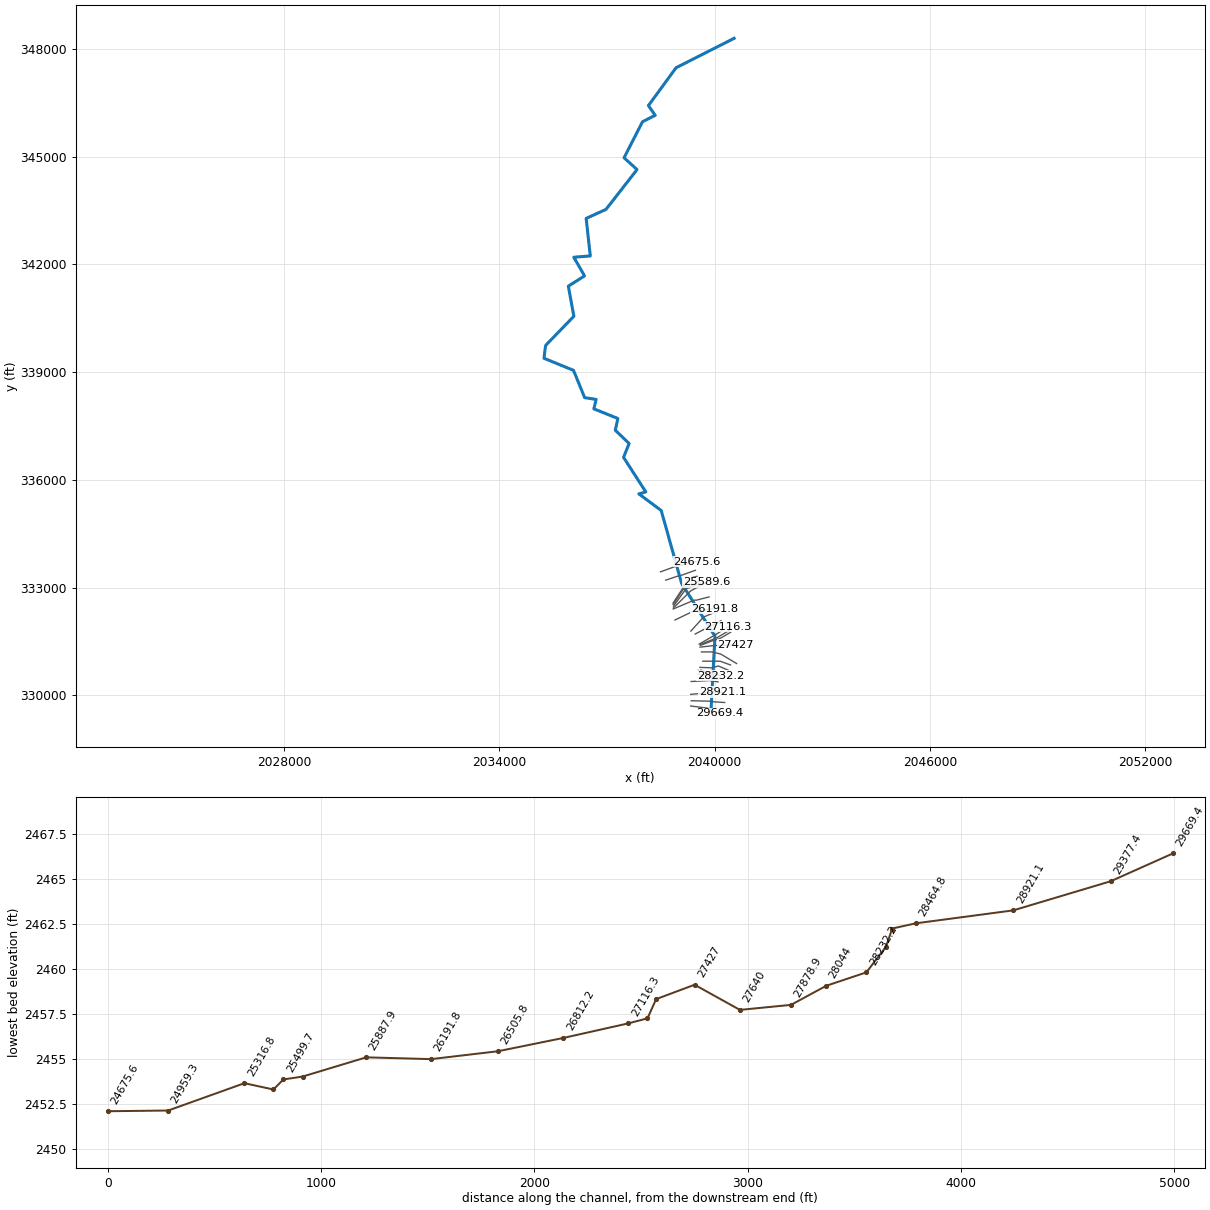
--- BOGGSCK.prj (project) ---

Proj Title=BOGGSCK
Current Plan=p01
Default Exp/Contr=0,0
English Units
Geom File=g01
Flow File=f01
Plan File=p01
BEGIN DESCRIPTION:
Stream Name- Boggs Creek
Flood Zone: Zone A
Greenbrier County, WV
County-Wide Study
WVDHSEM-2018-3, Flood Risk Project
HEC-RAS Version: 5.0.7
General Notes:
For the Hydrology Regression was used.
END DESCRIPTION:
DSS Export Rating Curves= 0
DSS Export Rating Curve Sorted= 0
DSS Export Volume Flow Curves= 0
DXF OffsetX= 0
DXF OffsetY= 0
DXF ScaleX= 0
DXF ScaleY= 0

--- BOGGSCK.p01 (plan) ---

Plan Title=Floodplain
Program Version=5.07
Short Identifier=Floodplain
Geom File=g01
Flow File=f01
Subcritical Flow
K Sum by GR= 0
Std Step Tol= 0.01
Critical Tol= 0.01
Num of Std Step Trials= 20
Max Error Tol= 0.3
Flow Tol Ratio= 0.001
Split Flow NTrial= 30
Split Flow Tol= 0.02
Split Flow Ratio= 0.02
Log Output Level= 0
Friction Slope Method= 1
Unsteady Friction Slope Method= 2
Unsteady Bridges Friction Slope Method= 1
Parabolic Critical Depth
Global Vel Dist= 0 , 0 , 0
Global Log Level= 0
CheckData=False
Encroach Param=-1 ,0,0, 0
Mapping Interval=1HOUR
Computation Time Step Use Courant=        0
Computation Time Step Use Time Series=    0
Computation Time Step Count To Double=0
Computation Time Step Max Doubling=0
Computation Time Step Max Halving=0
Computation Time Step Residence Courant=0
Run HTab= 0
Run UNet= 0
Run Sediment= 0
Run PostProcess= 0
Run WQNet= 0
Run RASMapper= 0
UNET Theta= 0
UNET Theta Warmup= 0
UNET ZTol= 0
UNET ZSATol= 0
UNET MxIter= 0
UNET Max Iter WO Improvement= 0
UNET MaxInSteps= 0
UNET DtIC= 0
UNET DtMin= 0
UNET MaxCRTS= 0
UNET WFStab= 0
UNET SFStab= 0
UNET WFX= 1
UNET SFX= 1
UNET 1D Methodology=Finite Difference
UNET DSS MLevel= 1
UNET Pardiso=0
UNET DZMax Abort= 0
UNET Use Existing IB Tables= 0
UNET Froude Reduction=False
UNET Froude Limit= 0
UNET Froude Power= 0
UNET D1 Cores= 0
UNET D2 Coriolis=0
UNET D2 Cores= 0
UNET D2 Theta= 1
UNET D2 Theta Warmup= 1
UNET D2 Z Tol= 0.01
UNET D2 Volume Tol= 0.01
UNET D2 Max Iterations= 20
UNET D2 Equation= 0
UNET D2 RampUpFraction=0.1
UNET D2 TimeSlices= 1
UNET D2 BCVolumeCheck=0
UNET D1D2 MaxIter= 0
UNET D1D2 ZTol=0.01
UNET D1D2 QTol=0.1
UNET D1D2 MinQTol=1
Write IC File= 0
Write IC File at Fixed DateTime=0
Write IC File at Sim End=0
Echo Input=False
Echo Parameters=False
Echo Output=False
Write Detailed= 0
HDF Write Warmup=0
HDF Write Time Slices=0
HDF Flush=0
HDF Face Node Velocities=0
HDF Compression= 1
HDF Chunk Size= 1
HDF Spatial Parts= 1
HDF Use Max Rows=0
HDF Fixed Rows= 1
Calibration Method= 0
Calibration Iterations= 20
Calibration Max Change=0.05
Calibration Tolerance=0.2
Calibration Maximum=1.5
Calibration Minimum=0.5
Calibration Optimization Method= 1
WQ AD Non Conservative
WQ ULTIMATE=-1
WQ Max Comp Step=1HOUR
WQ Output Interval=15MIN
WQ Output Selected Increments= 0
WQ Output face flow=0
WQ Output face velocity=0
WQ Output face area=0
WQ Output face dispersion=0
WQ Output cell volume=0
WQ Output cell surface area=0
WQ Output cell continuity=0
WQ Output cumulative cell continuity=0
WQ Output face conc=0
WQ Output face dconc_dx=0
WQ Output face courant=0
WQ Output face peclet=0
WQ Output face adv mass=0
WQ Output face disp mass=0
WQ Output cell mass=0
WQ Output cell source sink temp=0
WQ Output nsm pathways=0
WQ Output nsm derived pathways=0
WQ Output MaxMinRange=-1
WQ Daily Max Min Mean=-1
WQ Daily Range=0
WQ Daily Time=0
WQ Create Restart=0
WQ Fixed Restart=0
WQ System Summary=0
WQ Write To DSS=0
WQ Use Fixed Temperature=0
Sorting and Armoring Iterations= 10
XS Update Threshold= 0.02
Bed Roughness Predictor= 0
Hydraulics Update Threshold= 0.02
Energy Slope Method= 1
Volume Change Method= 1
Sediment Retention Method= 0
XS Weighting Method= 0
Number of US Weighted Cross Sections= 1
Number of DS Weighted Cross Sections= 1
Upstream XS Weight=0
Main XS Weight=1
Downstream XS Weight=0
Number of DS XS's Weighted with US Boundary= 1
Upstream Boundary Weight= 1
Weight of XSs Associated with US Boundary= 0
Number of US XS's Weighted with DS Boundary= 1
Downstream Boundary Weight= 0.5
Weight of XSs Associated with DS Boundary= 0.5
Percentile Method= 0
Sediment Output Level= 3
Mass or Volume Output= 0
Output Increment Type= 1
Profile and TS Output Increment= 1
XS Output Flag= 0
XS Output Increment= 10
Write Gradation File= 0
Read Gradation Hotstart= 0
Write HDF5 File= 1
Write Binary Output= 1
Write DSS Sediment File= 0
SV Curve= 0
Specific Gage Flag= 0

--- BOGGSCK.f01 (steady flow) ---

Flow Title=NFF Regression Equation
Program Version=5.07
Number of Profiles= 6
Profile Names=f1p,f10p,f4p,f2p,f02p,f1pplus
River Rch & RM=BOGGSCK,Main            ,29669.4
     551     291     387     466     770     815
River Rch & RM=BOGGSCK,Main            ,27116.3
     659     350     464     559     918     975
River Rch & RM=BOGGSCK,Main            ,24959.3
     925     498     656     786    1280    1370
River Rch & RM=BOGGSCK,Main            ,23765.4
    1190     648     850    1020    1640    1760
River Rch & RM=BOGGSCK,Main            ,20964.4
    1330     725     949    1130    1830    1960
River Rch & RM=BOGGSCK,Main            ,13830.2
    1500     822    1070    1280    2060    2220
River Rch & RM=BOGGSCK,Main            ,12377
    1670     919    1200    1430    2290    2470
River Rch & RM=BOGGSCK,Main            ,6260.8
    1880    1040    1350    1610    2570    2780
Boundary for River Rch & Prof#=BOGGSCK,Main            , 1
Up Type= 0
Dn Type= 3
Dn Slope=0.00185
Boundary for River Rch & Prof#=BOGGSCK,Main            , 2
Up Type= 0
Dn Type= 3
Dn Slope=0.00185
Boundary for River Rch & Prof#=BOGGSCK,Main            , 3
Up Type= 0
Dn Type= 3
Dn Slope=0.00185
Boundary for River Rch & Prof#=BOGGSCK,Main            , 4
Up Type= 0
Dn Type= 3
Dn Slope=0.00185
Boundary for River Rch & Prof#=BOGGSCK,Main            , 5
Up Type= 0
Dn Type= 3
Dn Slope=0.00185
Boundary for River Rch & Prof#=BOGGSCK,Main            , 6
Up Type= 0
Dn Type= 3
Dn Slope=0.00185
DSS Import GetInterval= 0
DSS Import GetPeak= 0
DSS Import FillOption= 0

--- BOGGSCK.g01 (geometry) ---

Geom Title=USGS 10m DEM
Program Version=5.07

River Reach=BOGGSCK         ,Main
Reach XY= 30
     2039897.093       329576.16     2040008.521      331643.828
     2039078.353      333114.837     2038510.594      335144.363
      2037886.71      335607.865     2038080.937      335662.118
     2037461.363       336623.49     2037615.443       337010.86
     2037230.243      337379.783     2037302.824      337705.581
     2036634.283      337974.915     2036697.474      338236.988
     2036377.378      338286.901     2036067.049       339046.45
     2035243.481      339383.907     2035290.139      339740.894
     2036076.906      340552.466     2035922.663      341390.854
     2036374.123      341676.658     2036074.644      342196.407
     2036534.714      342232.214     2036419.696      343277.136
     2036973.082      343528.872     2037836.797      344636.728
     2037475.301      344965.158     2037989.792      345970.278
     2038343.524      346147.144     2038153.637      346418.412
     2038924.036      347472.014      2040540.56      348290.728

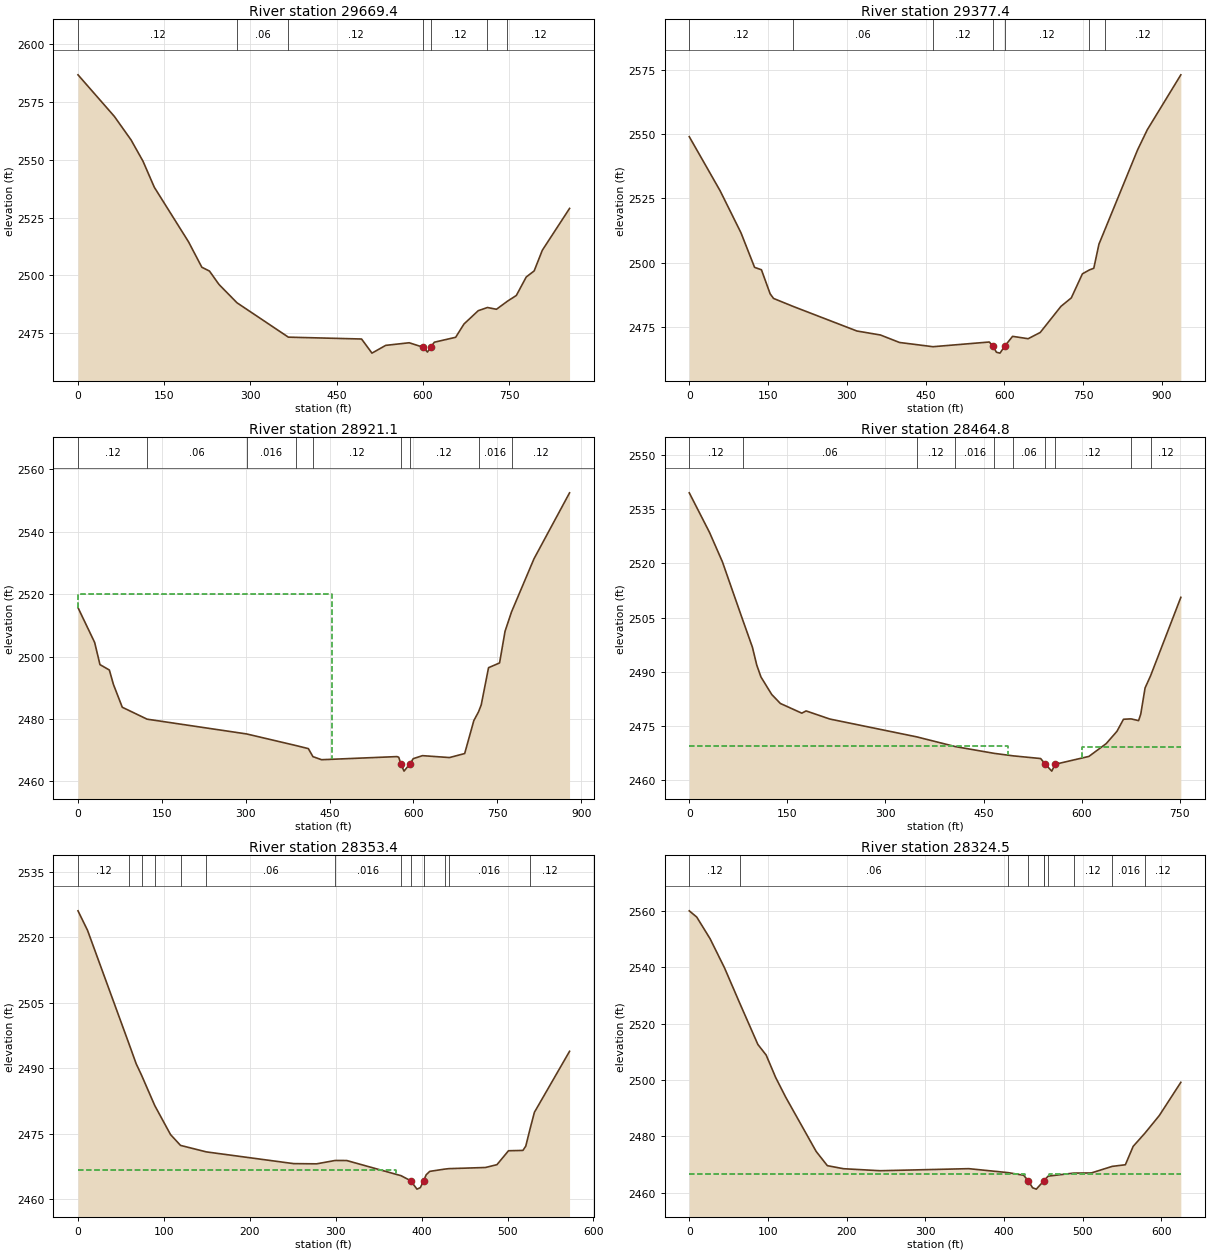
Type RM Length L Ch R = 1 ,29669.4 ,272,292,305.9
XS GIS Cut Line= 6
     2039329.022       329702.12     2039788.894      329642.678
     2039875.045      329617.385     2039936.099      329575.411
     2039998.203      329545.653     2040149.172      329496.162
#Sta/Elev= 30
       0 2586.65    63.3 2568.68    92.4  2558.5     113 2549.39   132.8 2538.08
   192.4 2514.48   215.5 2503.53   228.8 2501.87   245.3  2496.1  276.672488.177
  366.022473.329   493.4 2472.53   511.5 2466.43   535.4 2469.78   576.3 2470.91
   600.1 2469.01   608.1 2466.89  613.55 2469.01   620.1 2471.15   657.1 2473.27
   671.6 2479.01   696.4 2484.76  712.442486.139   728.1 2485.37  747.242488.865
   762.7 2491.34   779.9 2499.31   793.7 2501.94   807.9 2510.87   855.3 2528.94
#Mann= 7 ,-1 , 0
       0     .12       0  276.67     .06       0  366.02     .12       0
   600.1    .045       0  613.55     .12       0  712.44    .016       0
  747.24     .12       0
Bank Sta=600.1,613.55
XS Rating Curve= 0 ,0
Exp/Cntr=0.3,0.1

Type RM Length L Ch R = 1 ,29377.4 ,396.9,456.3,345
XS GIS Cut Line= 4
     2039346.295      329847.784     2039901.149      329835.345
     2039959.773      329819.145     2040279.076      329798.435
#Sta/Elev= 30
       0 2548.97    58.7 2527.97    98.5  2511.6   124.3 2498.21   137.4 2497.26
   153.9 2487.95   160.4 2486.13  198.092482.999   319.2 2473.47   363.9 2471.93
   400.2 2469.02  463.992467.373   571.2  2469.2     578 2467.62   584.8 2465.22
   591.5 2464.88   600.82467.645   615.5  2471.4   645.1 2470.48   668.1  2472.9
   707.5 2483.03   727.3 2486.34   748.4 2495.68  761.892497.221   770.1 2497.85
   779.9 2507.21  791.492512.973   853.4 2543.82   871.9 2551.65   935.8    2573
#Mann= 7 ,-1 , 0
       0     .12       0  198.09     .06       0  463.99     .12       0
     578    .045       0   600.8     .12       0  761.89    .016       0
  791.49     .12       0
Bank Sta=578,600.8
XS Rating Curve= 0 ,0
Exp/Cntr=0.3,0.1

Type RM Length L Ch R = 1 ,28921.1 ,374.9,456.3,386.4
XS GIS Cut Line= 4
     2039332.665      330025.681     2039885.963      330076.559
      2039946.38      330080.799      2040209.25      330089.279
#Sta/Elev= 30
       0 2515.68    29.8 2504.52    39.3 2497.42    56.1 2495.68    63.4 2491.05
    79.2 2483.74  123.572479.922  301.552475.185  390.532471.434     412 2470.48
  420.192467.911   435.6 2466.92   570.6 2467.92   573.7 2467.71  577.73  2465.4
   583.2 2463.26   593.72465.613   599.7 2467.27   616.2 2468.22   664.4 2467.61
   691.6  2468.9     708 2479.47  716.332482.249   721.2 2484.49   734.3 2496.43
     754 2497.95   763.8 2508.09  775.442514.333   815.6 2531.36   879.2  2552.5
#Mann= 9 ,-1 , 0
       0     .12       0  123.57     .06       0  301.55    .016       0
  390.53     .06       0  420.19     .12       0  577.73    .045       0
   593.7     .12       0  716.33    .016       0  775.44     .12       0
#XS Ineff= 2 , 0
             455    2520
Permanent Ineff=
       F       F
Bank Sta=577.73,593.7
XS Rating Curve= 0 ,0
Exp/Cntr=0.3,0.1

Type RM Length L Ch R = 1 ,28464.8 ,127.3,111.4,88.1
XS GIS Cut Line= 4
      2039344.61      330383.184     2039863.184      330410.658
     2039918.133      330396.062     2040092.421      330374.408
#Sta/Elev= 30
       0 2539.51    30.9 2528.59    50.6 2520.47   81.682504.395    96.6  2496.8
   103.2 2491.88   109.7 2488.56   126.1 2483.74   139.3 2481.26   172.1 2478.57
   178.7 2479.19   214.9 2476.95  347.892472.016  407.05 2469.32   466.2 2467.46
  495.782466.757   537.4 2466.02   544.2 2464.52   554.4 2462.54   559.72464.438
   611.2 2466.61   637.6 2470.14   654.1 2473.55   664.1 2476.89  675.71 2476.99
   687.2 2476.51   690.5  2478.3   697.1 2485.54  705.47 2488.88   751.8  2510.6
#Mann= 10 ,-1 , 0
       0     .12       0   81.68     .06       0  347.89     .12       0
  407.05    .016       0   466.2     .12       0  495.78     .06       0
   544.2    .045       0   559.7     .12       0  675.71    .016       0
  705.47     .12       0
#XS Ineff= 2 , 0
          487.49 2469.39  600.52         2469.08
Permanent Ineff=
       F       F
Bank Sta=544.2,559.7
XS Rating Curve= 0 ,0
Exp/Cntr=0.5,0.3

Type RM Length L Ch R = 1 ,28353.4 ,34.4,28.9,27.6
XS GIS Cut Line= 4
     2039544.977      330587.463     2039900.346      330524.178
     2039978.235      330468.543      2040091.42      330445.257
#Sta/Elev= 30
       0 2526.08    11.1 2521.61   59.342495.595    67.7 2491.02   74.112488.326
   89.342481.424   107.7 2474.77  119.342472.281  149.352470.792     251  2468.1
   277.7 2468.05  299.362468.821   312.8 2468.81  376.062465.332   387.12464.197
   394.6 2462.25   398.5 2462.59  402.24 2464.13   405.3 2465.54   409.4 2466.32
  426.882466.845  431.622466.946   474.3 2467.21   487.7 2467.86   501.1 2471.05
   517.9 2471.13   521.2  2472.1  526.33 2476.15   531.3 2479.88   572.2 2493.86
#Mann= 13 ,-1 , 0
       0     .12       0   59.34     .06       0   74.11     .12       0
   89.34     .06       0  119.34     .12       0  149.35     .06       0
  299.36    .016       0  376.06     .12       0   387.1    .045       0
  402.24    .016       0  426.88     .12       0  431.62    .016       0
  526.33     .12       0
#XS Ineff= 2 , 0
          370.16 2466.61  422.63         2466.68
Permanent Ineff=
       F       F
Bank Sta=387.1,402.24
XS Rating Curve= 0 ,0
Exp/Cntr=0.5,0.3

Type RM Length L Ch R = 1 ,28324.5 ,73.2,92.3,116
XS GIS Cut Line= 5
     2039543.798      330694.843     2039921.969      330544.176
     2039962.675      330514.701     2039991.496      330492.352
     2040120.993      330472.922
#Sta/Elev= 30
       0 2560.13     9.5 2557.91    26.4 2550.25    44.8 2539.86   64.15 2527.32
    87.2 2512.65    97.8 2508.85   109.8 2500.92   122.5 2493.95   161.3 2474.63
   175.5 2469.58   196.1 2468.49   242.6 2467.78   355.2 2468.51  405.032467.108
     425 2466.18   430.82464.201   436.4 2461.72   441.1 2461.24     4512464.272
  451.372464.422  456.152465.854   488.62466.935   511.1 2466.99  537.542469.324
   554.3  2469.9   564.2 2476.43  579.252481.155   597.4 2487.38   624.8 2499.19
#Mann= 10 ,-1 , 0
       0     .12       0   64.15     .06       0  405.03    .016       0
   430.8    .045       0     451    .016       0  451.37     .12       0
  456.15    .016       0   488.6     .12       0  537.54    .016       0
  579.25     .12       0
#XS Ineff= 2 , 0
          426.36 2466.54  457.49         2466.58
Permanent Ineff=
       F       F
Bank Sta=430.8,451
XS Rating Curve= 0 ,0
Exp/Cntr=0.5,0.3

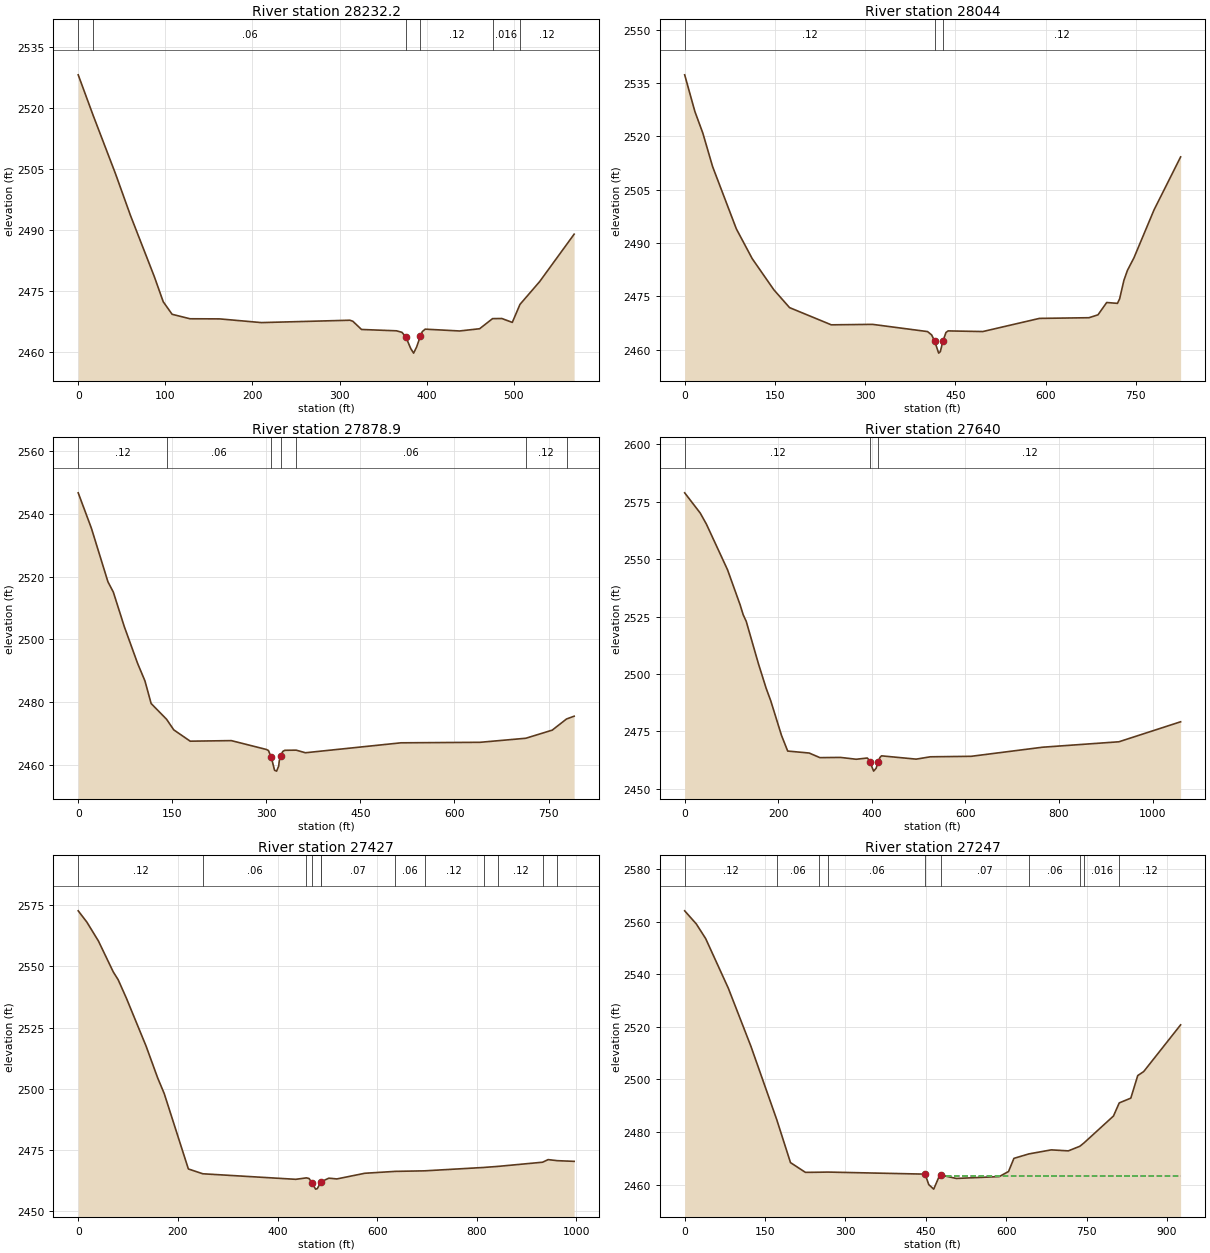
Type RM Length L Ch R = 1 ,28232.2 ,188.4,188.4,188.4
XS GIS Cut Line= 4
     2039616.347      330700.919     2039891.088       330621.74
     2040028.459      330599.799     2040163.921      330550.193
#Sta/Elev= 30
       0 2528.17   17.262518.144    42.9 2503.82      60 2493.62    87.3 2478.64
    97.6 2472.43   107.8 2469.35   128.3 2468.25   162.4 2468.22   210.2 2467.31
   311.9 2467.89   315.3 2467.63   325.2 2465.62   365.5 2465.29   371.7 2464.91
   376.2 2463.73   381.7 2460.94     385 2459.81   388.4 2461.28   392.7 2463.91
     395  2465.1   398.3  2465.7   437.7 2465.25   460.8  2465.8  475.662468.289
   486.3 2468.31   498.3 2467.36  507.112471.777   529.7 2477.38   569.3 2489.03
#Mann= 6 ,-1 , 0
       0     .12       0   17.26     .06       0   376.2    .045       0
   392.7     .12       0  475.66    .016       0  507.11     .12       0
Bank Sta=376.2,392.7
XS Rating Curve= 0 ,0
Exp/Cntr=0.3,0.1

Type RM Length L Ch R = 1 ,28044   ,164.9,164.9,164.9
XS GIS Cut Line= 4
2039588.11627303330777.1792936152039917.80341265330763.873534617
2040104.08403862330815.6181529432040380.54814225 330695.86632196
#Sta/Elev= 30
       0 2537.34      17 2527.01    30.1 2520.99    46.5 2511.49    85.9 2494.02
   112.2 2485.66   148.3 2476.87   174.4 2471.86   243.8 2467.02   312.5 2467.15
   403.8 2465.12   410.6 2464.19   415.6 2462.44   422.3 2459.06     425 2459.46
  429.39 2462.41   434.4 2464.85   437.9 2465.31   495.7 2465.13   589.9 2468.83
   672.2 2469.02   687.2 2469.83   701.7  2473.3   719.6 2473.06   723.2 2474.34
   730.3 2479.53   736.1 2482.31   747.1 2485.91   780.4 2499.35   824.6 2514.25
#Mann= 3 , 0 , 0
       0     .12       0   415.6    .045       0  429.39     .12       0
Bank Sta=415.6,429.39
XS Rating Curve= 0 ,0
Exp/Cntr(USF)=0,0
Exp/Cntr=0.3,0.1

Type RM Length L Ch R = 1 ,27878.9 ,239.4,239.4,239.4
XS GIS Cut Line= 4
     2039669.275      330948.524     2039920.132      330949.702
     2040150.968      330948.524     2040441.867      330843.706
#Sta/Elev= 30
       0 2546.76    21.1 2535.43    47.4 2518.39      56  2515.1    73.6 2504.03
    94.7 2492.37   106.4 2486.79   116.3 2479.56  140.882474.546   152.4 2471.16
   178.6 2467.55   244.2 2467.73     300 2464.91   303.3 2464.59     308 2462.38
   313.1 2458.28   316.4    2458   319.7 2459.61  320.63 2461.26   322.92462.771
   326.2 2464.28   329.5 2464.64  347.642464.689   362.3 2463.86   514.8 2467.03
   640.8 2467.19  713.772468.483   755.9 2471.07  778.752474.631   790.9 2475.52
#Mann= 7 ,-1 , 0
       0     .12       0  140.88     .06       0     308    .045       0
   322.9     .12       0  347.64     .06       0  713.77     .12       0
  778.75    .016       0
Bank Sta=308,322.9
XS Rating Curve= 0 ,0
Exp/Cntr=0.3,0.1

Type RM Length L Ch R = 1 ,27640   ,212.5,212.5,212.5
XS GIS Cut Line= 4
2039630.99038536331207.3988345552039917.80341265331207.398834555
2040167.65599828331148.2621278972040611.18129822  330883.6253656
#Sta/Elev= 30
       0 2578.92    33.2 2570.12    46.3 2565.35    91.6 2545.41   118.5 2530.15
     125 2525.86   131.6 2522.92   157.8 2504.39   174.2 2493.76   184.1 2488.27
     207 2473.25   220.2 2466.46   266.1  2465.6     289  2463.6   333.1 2463.69
   366.7 2462.89   390.3 2463.43     397 2461.88  398.95 2460.22   403.8 2457.72
   409.2 2458.97   413.9 2461.82   417.2 2463.61   420.6 2464.38   494.8 2462.94
   525.1 2463.96   612.3 2464.17   764.8 2468.13   928.1  2470.5    1060 2479.21
#Mann= 3 , 0 , 0
       0     .12       0     397    .045       0   413.9     .12       0
Bank Sta=397,413.9
XS Rating Curve= 0 ,0
Exp/Cntr(USF)=0,0
Exp/Cntr=0.3,0.1

Type RM Length L Ch R = 1 ,27427   ,180.3,180.3,180.3
XS GIS Cut Line= 4
      2039590.98      331341.417     2040037.558      331389.635
     2040095.249      331380.286     2040582.425      331405.389
#Sta/Elev= 30
       0 2572.63    17.5 2567.99    40.6 2560.31    70.3 2547.74    80.2 2544.52
    96.7    2537   136.3 2517.42   159.4 2504.52   172.6 2498.12   221.1 2467.35
  250.15 2465.38   436.6 2463.12  458.182463.712   463.3 2463.45   469.32461.691
   476.4 2459.12   479.7 2459.29   486.92461.923   488.12462.173     503 2463.59
   519.2 2463.28   575.3 2465.59  636.212466.359  695.362466.581  813.662467.954
  843.242468.404  931.972470.095   943.2 2471.16  961.552470.726   995.4 2470.45
#Mann= 12 ,-1 , 0
       0     .12       0  250.15     .06       0  458.18     .12       0
   469.3    .045       0   486.9     .12       0   488.1     .07       0
  636.21     .06       0  695.36     .12       0  813.66     .06       0
  843.24     .12       0  931.97    .016       0  961.55     .06       0
Bank Sta=469.3,486.9
XS Rating Curve= 0 ,0
Exp/Cntr=0.5,0.3

Type RM Length L Ch R = 1 ,27247   ,40.6,40.6,40.6
XS GIS Cut Line= 5
2039601.22725095331388.9986027642039981.52843261331533.575911492
2040064.84739273331556.4285552262040171.38986881331594.233949966
2040446.33819419331755.766091127
#Sta/Elev= 30
       0  2564.1    21.7 2559.12    39.2 2553.53    81.4  2534.7   123.7 2512.54
     172 2484.59   197.4  2468.4   225.3 2464.69   249.8 2464.74   267.4  2464.8
   448.5 2464.02   455.4 2460.02   464.6 2458.32   475.3 2463.41   478.52463.633
   506.7 2462.38   586.8 2463.08   604.2 2465.02   614.2 2470.01     642  2471.7
   683.9 2473.24   715.7 2472.86   737.2 2474.61   744.8 2475.86   799.9  2486.1
   810.7 2491.09   832.3 2492.91   845.2 2501.48   856.3    2503   925.2 2520.76
#Mann= 10 ,-1 , 0
       0     .12       0     172     .06       0   249.8    .016       0
   267.4     .06       0   448.5    .045       0   478.5     .07       0
     642     .06       0   737.2     .12       0   744.8    .016       0
   810.7     .12       0
#XS Ineff= 2 , 0
          433.83 2463.18  490.08          2463.2
Permanent Ineff=
       F       F
Bank Sta=448.5,478.5
XS Rating Curve= 0 ,0
Exp/Cntr(USF)=0,0
Exp/Cntr=0.5,0.3

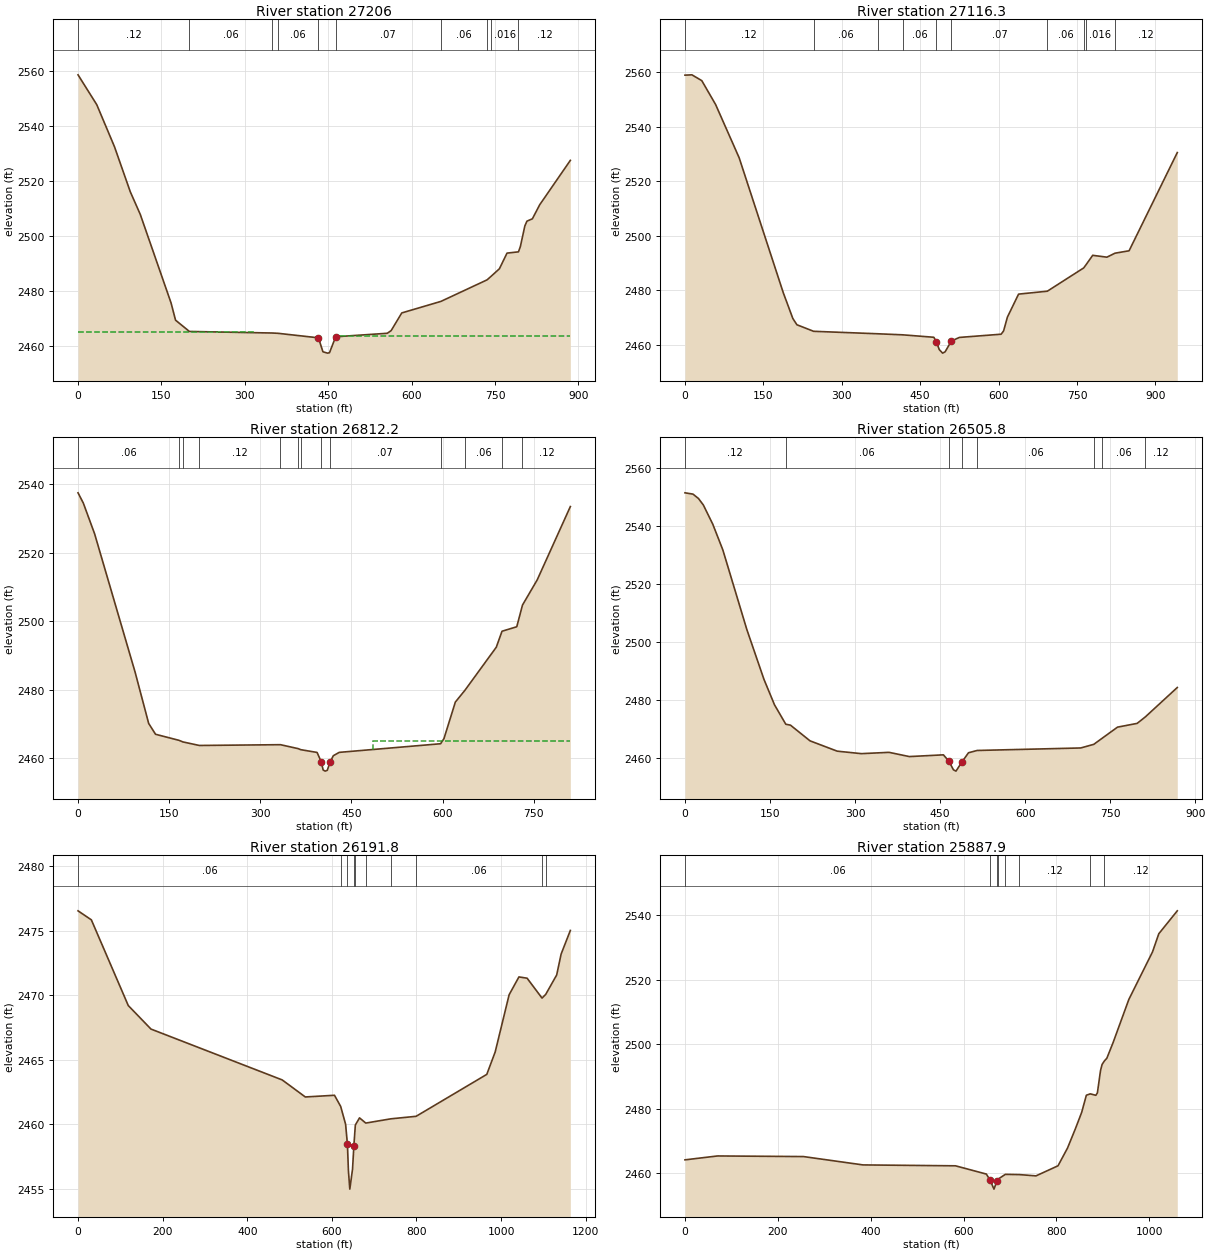
Type RM Length L Ch R = 1 ,27206   ,89.8,89.8,89.8
XS GIS Cut Line= 4
2039610.03703783331416.6631564912039993.81907534331573.612825562
2040069.42986482331606.8357482122040403.95032737331803.882048068
#Sta/Elev= 30
       0 2558.67    33.7 2547.79    65.6 2532.45    93.9  2516.1     112 2507.78
   167.3 2475.56   175.4 2469.26   200.3 2465.15   349.1 2464.58   359.8 2464.47
   432.4 2462.83   440.5 2457.74   448.7 2457.25   452.3 2457.39   463.4 2463.21
   556.1 2464.48   563.2 2465.46   582.3  2471.9   652.7  2476.1   735.7 2483.95
   742.7  2485.2   757.9 2487.99   771.6  2493.7   792.2 2494.16   795.6 2496.08
   803.6 2503.55   807.4 2505.34   817.2 2506.19   830.3 2511.29   885.5  2527.5
#Mann= 10 ,-1 , 0
       0     .12       0   200.3     .06       0   349.1    .016       0
   359.8     .06       0   432.4    .045       0   463.4     .07       0
   652.7     .06       0   735.7     .12       0   742.7    .016       0
   792.2     .12       0
#XS Ineff= 2 , 0
          318.64 2465.02  470.97          2463.4
Permanent Ineff=
       F       F
Bank Sta=432.4,463.4
XS Rating Curve= 0 ,0
Exp/Cntr(USF)=0,0
Exp/Cntr=0.5,0.3

Type RM Length L Ch R = 1 ,27116.3 ,312.5,304.1,293.3
XS GIS Cut Line= 3
     2039567.352      331424.563     2039994.505      331670.403
     2040375.658      331907.419
#Sta/Elev= 30
       0 2558.97    13.3 2559.09    32.2 2556.95    58.7 2548.16   103.6 2528.68
   188.1  2479.1   206.3 2469.69   214.1 2467.38  246.05 2464.98   368.32464.073
  416.452463.685     476 2462.79   480.8 2461.23   486.4 2458.27   492.8 2456.97
   497.6 2457.45   509.5 2461.41   524.9 2462.73   604.8 2463.91   609.5 2465.13
   616.7 2470.16   638.1 2478.62  693.132479.694   762.72488.235  766.762489.295
   779.9 2492.86     807 2492.18  822.692493.647   849.5 2494.52   941.7 2530.56
#Mann= 10 ,-1 , 0
       0     .12       0  246.05     .06       0   368.3    .016       0
  416.45     .06       0   480.8    .045       0   509.5     .07       0
  693.13     .06       0   762.7     .12       0  766.76    .016       0
  822.69     .12       0
Bank Sta=480.8,509.5
XS Rating Curve= 0 ,0
Exp/Cntr=0.3,0.1

Type RM Length L Ch R = 1 ,26812.2 ,280.9,306.4,331.3
XS GIS Cut Line= 4
     2039456.317      331704.959     2039796.948      331884.636
     2039841.645      331892.856     2040174.553      332075.729
#Sta/Elev= 30
       0 2537.48     8.7 2534.49    27.3  2525.5      94 2485.05   116.3 2470.09
   127.6 2466.93  166.272465.155  172.622464.693  199.662463.658  333.242463.885
  362.562462.724  366.632462.427   393.5 2461.62   400.2 2458.95   403.5 2456.49
   406.9 2456.16   410.3  2456.4   414.82458.763   420.2 2460.66   429.9 2461.64
  596.812464.162   602.4 2465.68   621.1 2476.34  637.042479.821   688.5 2492.37
  697.912497.033   722.2 2498.35  731.612504.676   755.9 2512.06   810.4 2533.46
#Mann= 13 ,-1 , 0
       0     .06       0  166.27     .12       0  172.62     .06       0
  199.66     .12       0  333.24     .06       0  362.56     .12       0
  366.63     .06       0   400.2    .045       0   414.8     .07       0
  596.81     .12       0  637.04     .06       0  697.91    .016       0
  731.61     .12       0
#XS Ineff= 2 , 0
                             485            2465
Permanent Ineff=
       F       F
Bank Sta=400.2,414.8
XS Rating Curve= 0 ,0
Exp/Cntr=0.3,0.1

Type RM Length L Ch R = 1 ,26505.8 ,354.6,314.1,267.4
XS GIS Cut Line= 4
     2039336.473      331787.108     2039630.534      332112.527
     2039689.978      332178.112     2040005.136      332309.303
#Sta/Elev= 30
       0 2551.44    14.1    2551    23.9 2549.47    32.5 2547.21    49.1  2540.6
    66.8 2531.75   109.1  2504.3   139.3 2487.11   157.9 2478.32  177.812471.612
   186.2 2471.27   220.6 2465.87   268.5 2462.31   311.2 2461.45     360  2461.9
   395.8 2460.44   455.9 2461.04   465.3 2458.93   473.6 2455.88   478.1 2455.42
   488.7 2458.62   500.2 2461.76  515.472462.546   698.2 2463.41  721.252464.668
  735.252466.664   763.1  2470.6   797.7 2471.89  812.112474.125   868.5 2484.27
#Mann= 8 ,-1 , 0
       0     .12       0  177.81     .06       0   465.3    .045       0
   488.7     .12       0  515.47     .06       0  721.25     .12       0
  735.25     .06       0  812.11     .12       0
Bank Sta=465.3,488.7
XS Rating Curve= 0 ,0
Exp/Cntr=0.3,0.1

Type RM Length L Ch R = 1 ,26191.8 ,299.5,303.9,308
XS GIS Cut Line= 4
     2038894.254      332096.833     2039440.146      332358.302
     2039511.569      332353.309     2039994.717       332412.92
#Sta/Elev= 30
       0 2476.54    31.5 2475.84   118.8  2469.2   172.4 2467.38   482.6 2463.44
   537.2 2462.12   606.2 2462.25  620.852461.386   632.5    2460  636.81 2458.44
   639.1 2456.42   642.4 2454.98   648.9 2456.54     6522458.349   654.12459.302
   655.5 2459.95   665.4  2460.5  680.092460.097  739.612460.427  799.132460.621
   966.2 2463.87     986  2465.6    1019 2470.04  1042.2 2471.42  1061.5 2471.32
 1096.74 2469.78 1105.422470.064  1131.4 2471.57  1141.9 2473.19  1163.7 2475.02
#Mann= 10 ,-1 , 0
       0     .06       0  620.85     .12       0  636.81    .045       0
     652     .12       0   654.1     .12       0  680.09     .06       0
  739.61     .12       0  799.13     .06       0 1096.74     .12       0
 1105.42    .016       0
Bank Sta=636.81,652
XS Rating Curve= 0 ,0
Exp/Cntr=0.3,0.1

Type RM Length L Ch R = 1 ,25887.9 ,281,298.2,320.9
XS GIS Cut Line= 4
     2038845.098      332403.032      2039429.08      332649.114
     2039491.843      332647.484     2039843.766      332738.796
#Sta/Elev= 30
       0 2464.16    70.2 2465.37   255.1 2465.18   383.3 2462.59   582.6 2462.31
     649 2459.75     657 2457.86   665.4 2455.08   671.82457.606   674.52458.209
  689.87 2459.66  720.162459.585   755.9 2459.19   803.3 2462.32   823.7 2467.81
   840.6 2473.77   854.2 2478.88   864.3 2484.21  872.742484.634   884.7 2484.18
   888.1 2484.95   894.8 2491.87   898.2 2493.77  903.262494.864   908.4 2495.67
     922 2500.59   955.8 2513.93  1006.7 2528.65  1020.3  2534.3  1060.1 2541.41
#Mann= 8 ,-1 , 0
       0     .06       0     657    .045       0   671.8     .12       0
   674.5     .12       0  689.87     .06       0  720.16     .12       0
  872.74    .016       0  903.26     .12       0
Bank Sta=657,671.8
XS Rating Curve= 0 ,0
Exp/Cntr=0.3,0.1

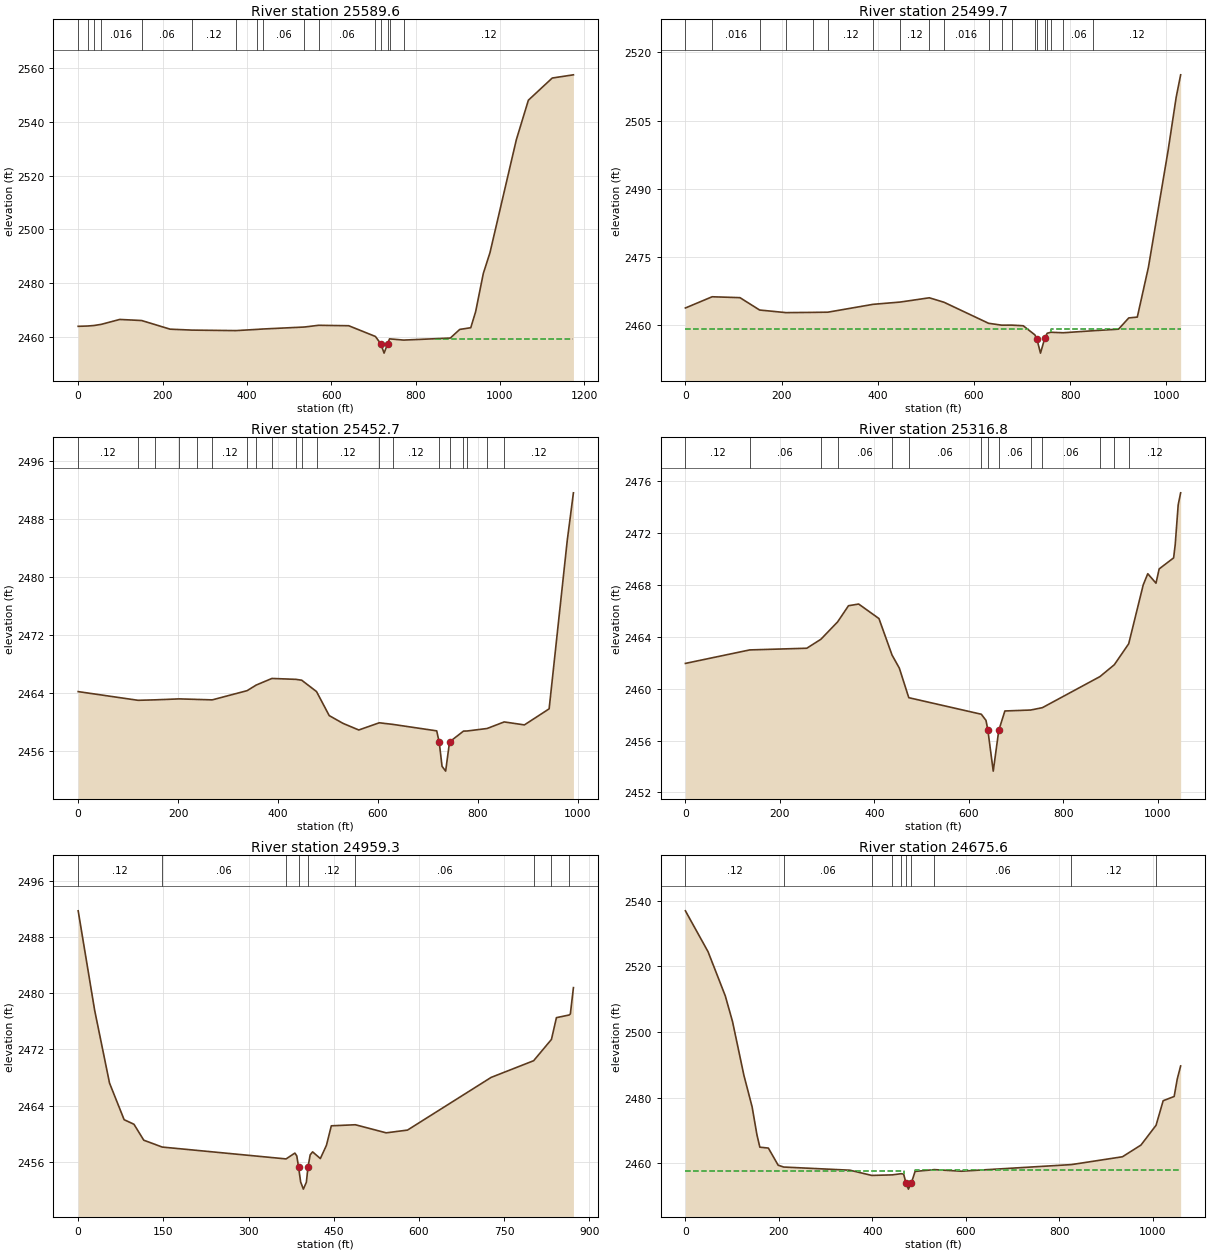
Type RM Length L Ch R = 1 ,25589.6 ,98.3,90,83.2
XS GIS Cut Line= 4
2038851.18463961 332431.47318698     2039329.937      332904.523
     2039415.913      332952.822     2039770.106      333143.905
#Sta/Elev= 30
       0 2463.98   22.72  2464.1   37.022464.271   54.662464.711    98.6 2466.54
  150.492466.137     218 2462.92  269.782462.572  374.092462.388  424.962462.844
  437.972462.983  536.232463.718  570.112464.363   641.4  2464.2  704.572460.216
   717.3 2457.53   725.2 2454.01   733.52457.389  738.132459.318  771.692458.862
   882.2 2459.61   904.6 2462.83   930.7 2463.46   942.3 2469.45   960.5 2483.66
   976.2 2491.35  1038.8 2533.41  1067.3 2548.09  1123.9 2556.34  1174.1 2557.53
#Mann= 16 ,-1 , 0
       0     .08       0   22.72    .016       0   37.02     .12       0
   54.66    .016       0  150.49     .06       0  269.78     .12       0
  374.09     .06       0  424.96     .12       0  437.97     .06       0
  536.23     .12       0  570.11     .06       0  704.57     .12       0
   717.3    .045       0   733.5     .12       0  738.13    .016       0
  771.69     .12       0
#XS Ineff= 2 , 0
                             845          2459.4
Permanent Ineff=
       F       F
Bank Sta=717.3,733.5
XS Rating Curve= 0 ,0
Exp/Cntr=0.5,0.3

Type RM Length L Ch R = 1 ,25499.7 ,46.2,47,48.7
XS GIS Cut Line= 5
2038852.10277448332483.6398306922039208.89566679332971.959949237
     2039295.536      332994.755      2039501.53      333076.939
     2039606.194      333120.669
#Sta/Elev= 30
       0 2463.78    55.62466.246   113.4 2466.05   154.3 2463.33     2092462.758
   265.62462.811   296.22462.855   390.32464.583   446.52465.082   507.12466.021
   537.6 2465.04   630.22460.416   657.3    2460   678.52460.009   702.3 2459.87
   726.42457.884   730.72456.957   738.2 2453.85   747.12457.122   752.1 2458.22
   759.72458.438   785.72458.332     8482458.778   900.5 2459.12   921.7 2461.59
   939.5 2461.78   962.6 2472.74  1003.5 2498.41  1020.3 2510.13  1029.6 2515.06
#Mann= 20 ,-1 , 0
       0     .12       0    55.6    .016       0   154.3     .06       0
     209     .12       0   265.6     .06       0   296.2     .12       0
   390.3    .016       0   446.5     .12       0   507.1     .08       0
   537.6    .016       0   630.2     .12       0   657.3     .06       0
   678.5    .016       0   726.4     .12       0   730.7    .045       0
   747.1     .12       0   752.1     .06       0   759.7    .016       0
   785.7     .06       0     848     .12       0
#XS Ineff= 2 , 0
          712.73  2459.2  759.48          2459.2
Permanent Ineff=
       F       F
Bank Sta=730.7,747.1
XS Rating Curve= 0 ,0
Exp/Cntr=0.5,0.3

Type RM Length L Ch R = 1 ,25452.7 ,106.1,135.9,168.9
XS GIS Cut Line= 5
2038843.80685977332527.2338967052039158.40711657333000.174139068
     2039237.329      333018.913     2039420.911      333099.244
     2039550.727      333155.651
#Sta/Elev= 30
       0 2464.23   119.82463.034   152.92463.095   202.52463.229   238.72463.154
   268.32463.094   338.12464.362   356.2 2465.13   387.7 2466.04   435.82465.917
   447.3  2465.8     4772464.236   502.4 2460.93     530 2459.86   561.6 2458.95
   602.62459.942   630.52459.714   717.5 2458.83   722.5 2457.28   728.2 2453.95
   735.4 2453.29   743.2 2457.31   771.12458.797   778.52458.813   818.42459.156
   852.52460.059     893 2459.65   942.5 2461.86   978.8 2485.06   991.1 2491.58
#Mann= 20 ,-1 , 0
       0     .12       0   119.8     .06       0   152.9    .016       0
   202.5     .08       0   238.7     .06       0   268.3     .12       0
   338.1     .08       0   356.2     .06       0   387.7    .016       0
   435.8     .12       0   447.3     .08       0     477     .12       0
   602.6    .016       0   630.5     .12       0   722.5    .045       0
   743.2     .12       0   771.1    .016       0   778.5     .12       0
   818.4    .016       0   852.5     .12       0
Bank Sta=722.5,743.2
XS Rating Curve= 0 ,0
Exp/Cntr=0.5,0.3

Type RM Length L Ch R = 1 ,25316.8 ,392.7,357.5,294.4
XS GIS Cut Line= 5
  2038840.457476332566.422385019     2039172.226      333074.643
     2039223.046      333158.5562039275.71874797 333251.13193282
2039504.59763961333311.556782693
#Sta/Elev= 30
       0 2461.95  136.162462.991   256.9 2463.12  286.772463.812  322.142465.151
   345.2  2466.4   366.8 2466.53   409.7 2465.41  437.382462.597   452.8 2461.59
  472.842459.306   626.42458.028   636.3 2457.55   640.1 2456.84   651.6 2453.64
   663.3 2456.78   676.2 2458.28  730.892458.354  755.672458.536  877.432460.932
  907.882461.848  938.322463.464     969    2468   978.7 2468.87   996.1 2468.14
  1002.8 2469.24  1033.4 2470.09  1036.8 2471.12  1043.1 2474.19  1048.3 2475.11
#Mann= 14 ,-1 , 0
       0     .12       0  136.16     .06       0  286.77     .12       0
  322.14     .06       0  437.38     .12       0  472.84     .06       0
   626.4     .12       0   640.1    .045       0   663.3     .06       0
  730.89     .12       0  755.67     .06       0  877.43     .12       0
  907.88    .016       0  938.32     .12       0
Bank Sta=640.1,663.3
XS Rating Curve= 0 ,0
Exp/Cntr=0.3,0.1

Type RM Length L Ch R = 1 ,24959.3 ,279.4,283.7,287.9
XS GIS Cut Line= 4
     2038636.017       333204.99     2038974.822      333319.048
     2039086.508      333345.691     2039462.534      333480.534
#Sta/Elev= 30
       0 2491.72      29 2477.57    55.2 2467.21    80.9    2462    98.2 2461.35
   115.5 2459.08  148.032458.105  365.972456.419   381.5 2457.25   384.8 2456.85
   387.92455.315   391.6 2453.14   396.4 2452.12   401.7  2453.1   404.5 2455.24
   408.4    2457   412.7 2457.42   426.3 2456.47     437 2458.35   445.6 2461.13
  487.94 2461.28   542.2 2460.13   579.7 2460.52     727 2468.02  801.73 2470.39
   833.1 2473.42   841.9 2476.52  864.482476.901   866.4 2477.05   871.8 2480.79
#Mann= 9 ,-1 , 0
       0     .12       0  148.03     .06       0  365.97     .12       0
   387.9    .045       0   404.5     .12       0  487.94     .06       0
  801.73     .12       0   833.1    .016       0  864.48     .12       0
Bank Sta=387.9,404.5
XS Rating Curve= 0 ,0
Exp/Cntr=0.5,0.3

Type RM Length L Ch R = 1 ,24675.6 ,46.6,38.5,32.2
XS GIS Cut Line= 4
     2038489.977      333436.752     2038890.653      333581.663
     2038986.754      333615.838     2039507.122      333723.997
#Sta/Elev= 30
       0 2536.94    48.5 2524.46    85.3 2511.02   100.8 2503.18   125.2 2486.76
   142.7 2477.19   153.1 2468.61   159.3 2464.87   177.5  2464.6   198.5 2459.37
  210.252458.816     352 2457.85  398.712456.257  442.782456.429  461.462456.781
   466.9 2456.67   471.92453.982   477.1 2452.08   483.6 2454.03   491.4 2457.48
  532.792458.025   590.5 2457.54  825.992459.561   935.1 2461.95   974.7 2465.52
    1007 2471.55  1022.2 2479.04  1045.7 2480.33  1052.4  2485.7  1059.6 2489.64
#Mann= 10 ,-1 , 0
       0     .12       0  210.25     .06       0  398.71     .12       0
  442.78     .06       0  461.46     .12       0   471.9    .045       0
   483.6     .12       0  532.79     .06       0  825.99     .12       0
    1007    .016       0
#XS Ineff= 2 , 0
          466.71 2457.49  491.49         2457.92
Permanent Ineff=
       F       F
Bank Sta=471.9,483.6
XS Rating Curve= 0 ,0
Exp/Cntr=0.5,0.3