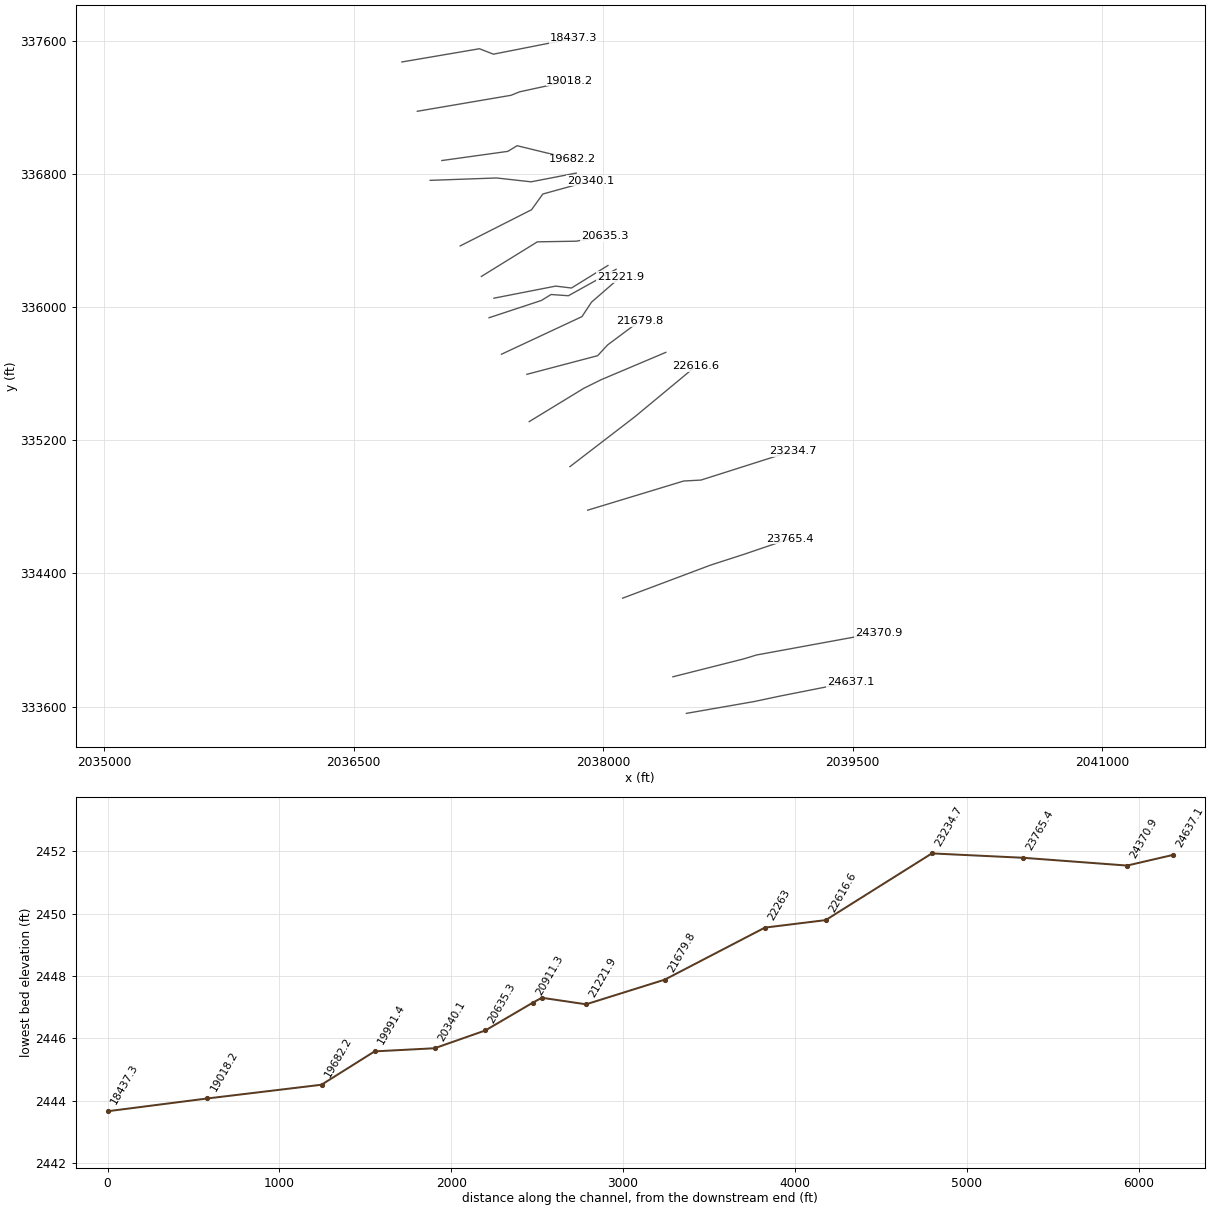
HEC-RAS study BOGGSCK.prj: BOGGSCK

--- BOGGSCK.g01 (geometry) --- (continued)

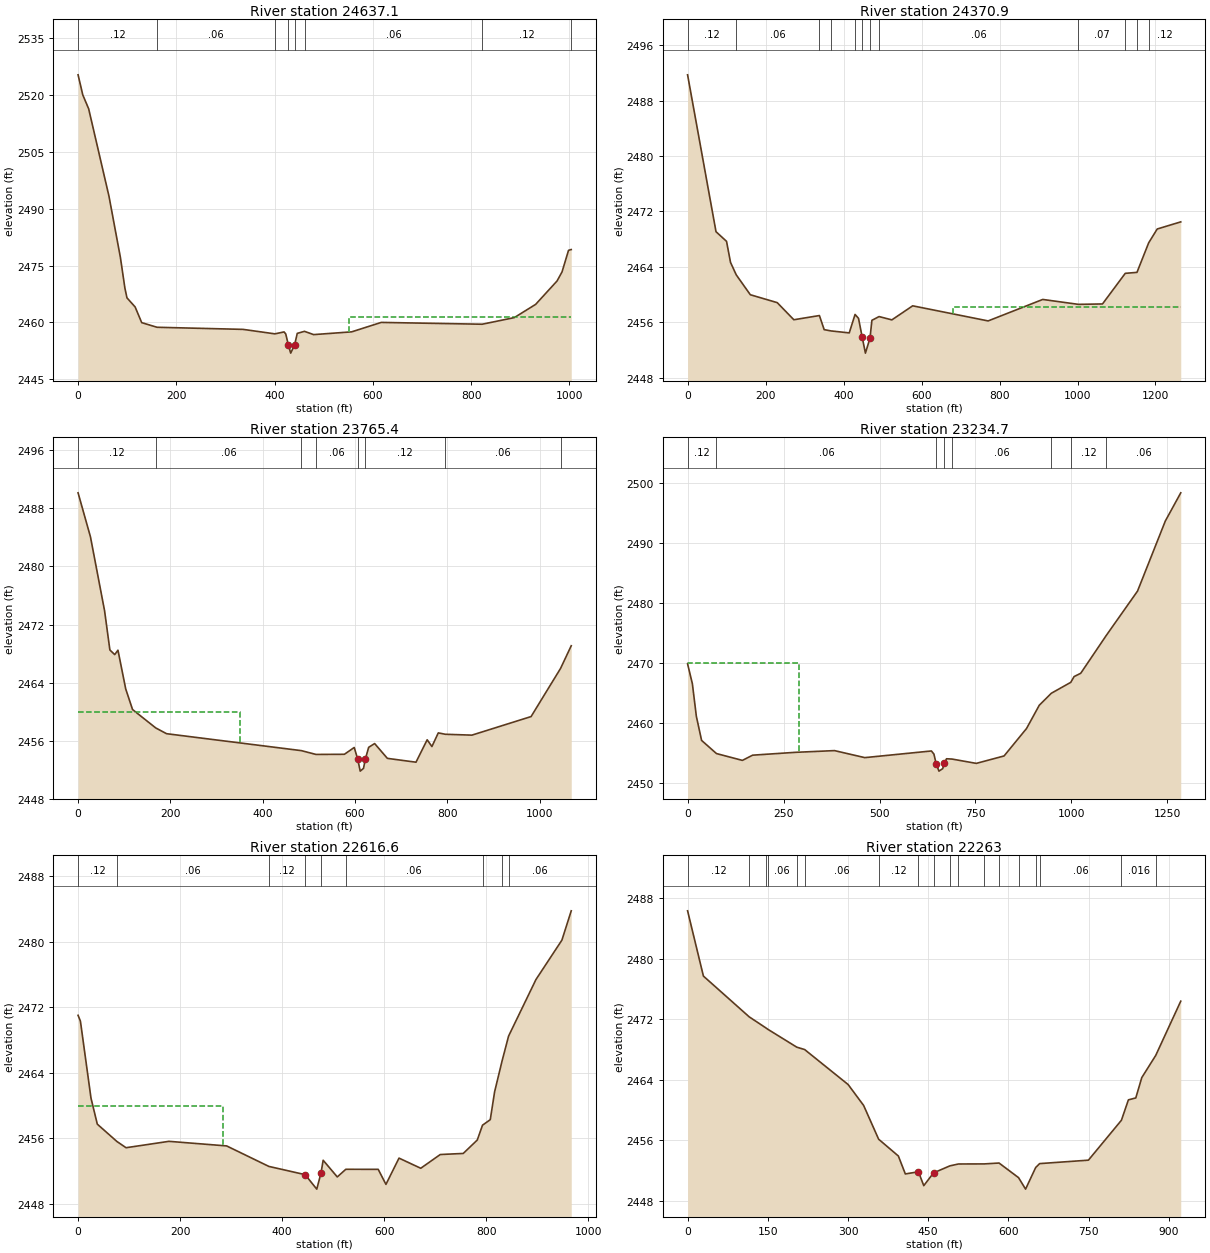
Type RM Length L Ch R = 1 ,24637.1 ,262.1,266.3,271.3
XS GIS Cut Line= 4
     2038499.875      333559.933     2038905.774      333630.686
     2039063.639      333664.068      2039485.77       333747.52
#Sta/Elev= 30
       0 2525.37     9.6 2520.07    21.6 2516.38    62.9 2493.31    86.2 2477.11
    95.3 2469.05    99.5 2466.48   116.1 2464.08   129.5 2459.93  160.672458.708
   335.9 2458.15  400.532456.971   419.2 2457.48   422.6 2456.96  428.04 2454.01
   432.7 2451.88  440.55 2453.99   446.1  2457.1  460.832457.632   479.4 2456.77
   556.9  2457.5     617 2459.99  822.442459.511   887.9 2461.26   931.3 2464.76
   974.8 2470.93   984.9 2473.31   998.2 2479.03 1003.092479.219  1003.7 2479.23
#Mann= 8 ,-1 , 0
       0     .12       0  160.67     .06       0  400.53     .12       0
  428.04    .045       0  440.55     .12       0  460.83     .06       0
  822.44     .12       0 1003.09    .016       0
#XS Ineff= 2 , 0
                          551.74         2461.47
Permanent Ineff=
       F       F
Bank Sta=428.04,440.55
XS Rating Curve= 0 ,0
Exp/Cntr=0.5,0.3

Type RM Length L Ch R = 1 ,24370.9 ,602,605.5,606
XS GIS Cut Line= 5
     2038418.959      333779.693      2038836.24      333885.067
     2038861.021      333892.018     2038921.037      333910.506
     2039654.748      334044.936
#Sta/Elev= 30
       0 2491.72    72.9 2469.07    99.9 2467.68   110.1 2464.64  124.842462.839
   160.9 2459.97   229.9 2458.83   272.5 2456.36  338.092456.965   350.3 2454.93
  368.562454.741   414.6 2454.46  429.492457.124   438.4 2456.56   447.9 2453.81
   456.1 2451.54   467.9 2453.73   472.7 2456.28   491.12456.817   523.9 2456.34
   577.3 2458.37   770.8 2456.19   910.8 2459.29 1002.382458.581  1064.1 2458.64
 1122.49 2463.06 1152.522463.199 1182.552467.467  1204.4 2469.46  1264.8 2470.49
#Mann= 12 ,-1 , 0
       0     .12       0  124.84     .06       0  338.09     .12       0
  368.56     .06       0  429.49     .12       0   447.9    .045       0
   467.9     .12       0   491.1     .06       0 1002.38     .07       0
 1122.49     .12       0 1152.52    .016       0 1182.55     .12       0
#XS Ineff= 2 , 0
                          681.74         2458.14
Permanent Ineff=
       F       F
Bank Sta=447.9,467.9
XS Rating Curve= 0 ,0
Exp/Cntr=0.3,0.1

Type RM Length L Ch R = 1 ,23765.4 ,542.3,530.7,517.8
XS GIS Cut Line= 4
     2038116.731      334251.788     2038645.664      334450.516
     2038848.253      334515.978     2039123.117      334609.433
#Sta/Elev= 30
       0 2490.15    26.8 2484.09    57.4  2473.9    68.9 2468.49    79.4 2467.85
    86.4 2468.46   103.2 2463.12     118 2460.28  168.172457.747   191.6 2456.95
  483.712454.615  515.262454.091   576.9 2454.11   598.2 2455.05   605.62453.471
   611.2 2451.79   618.3 2452.17  622.36 2453.47   629.5 2455.07   642.4 2455.59
     670 2453.55     732 2453.02   756.2 2456.11   766.5 2455.18   780.3 2457.06
  795.52 2456.87   853.1 2456.75   981.3 2459.31  1045.1 2465.94  1068.3 2469.07
#Mann= 8 ,-1 , 0
       0     .12       0  168.17     .06       0  483.71     .12       0
  515.26     .06       0   605.6    .045       0  622.36     .12       0
  795.52     .06       0  1045.1    .016       0
#XS Ineff= 2 , 0
             350    2460
Permanent Ineff=
       F       F
Bank Sta=605.6,622.36
XS Rating Curve= 0 ,0
Exp/Cntr=0.3,0.1

Type RM Length L Ch R = 1 ,23234.7 ,580.3,618.1,648
XS GIS Cut Line= 4
     2037906.742      334780.246       2038483.9      334955.381
     2038587.975       334961.16 2039138.3170578335136.067104549
#Sta/Elev= 30
       0 2469.81    12.5 2466.49    22.8 2461.08    36.5 2457.05   75.282454.857
   142.8 2453.72   169.5 2454.59   279.9 2455.06   382.8 2455.35   461.7 2454.18
   635.2 2455.29   641.7 2454.78   647.82453.107   654.9 2451.93   664.7 2452.35
     669 2453.29   674.6 2453.99   688.92453.942   752.2 2453.22   824.5 2454.46
     883 2459.03   916.2 2462.91  947.682464.912  998.212466.727  1006.9 2467.69
  1024.2 2468.24 1091.272474.594  1172.2 2481.94  1244.6 2493.62  1284.8 2498.32
#Mann= 8 ,-1 , 0
       0     .12       0   75.28     .06       0   647.8    .045       0
     669     .12       0   688.9     .06       0  947.68    .016       0
  998.21     .12       0 1091.27     .06       0
#XS Ineff= 2 , 0
             290    2470
Permanent Ineff=
       F       F
Bank Sta=647.8,669
XS Rating Curve= 0 ,0
Exp/Cntr=0.3,0.1

Type RM Length L Ch R = 1 ,22616.6 ,361.8,353.6,486.6
XS GIS Cut Line= 4
     2037800.258      335041.874     2038162.817      335320.176
2038194.66979026335344.921809688     2038556.043      335644.412
#Sta/Elev= 30
       0 2471.03     4.6 2470.32    25.3 2460.92    37.7 2457.73    76.12455.614
      94 2454.85   178.2 2455.63   291.2 2455.07  373.992452.565     445 2451.56
   467.9 2449.79   476.2 2451.76   480.4 2453.32   508.1 2451.28  524.782452.212
   588.3 2452.21   603.5 2450.37   629.1 2453.58   671.7 2452.34     710 2454.02
     755 2454.15   782.5 2455.79  792.762457.602     808 2458.28   816.5 2461.69
  831.042465.432  843.86 2468.49   897.5  2475.4   948.4 2480.22   966.7  2483.8
#Mann= 9 ,-1 , 0
       0     .12       0    76.1     .06       0  373.99     .12       0
     445    .045       0   476.2     .12       0  524.78     .06       0
  792.76    .016       0  831.04     .12       0  843.86     .06       0
#XS Ineff= 2 , 0
             285    2460
Permanent Ineff=
       F       F
Bank Sta=445,476.2
XS Rating Curve= 0 ,0
Exp/Cntr=0.3,0.1

Type RM Length L Ch R = 1 ,22263   ,178.9,583.2,215.5
XS GIS Cut Line= 4
     2037555.516      335312.303     2037884.103      335512.517
     2037988.921      335564.338     2038376.394      335728.042
#Sta/Elev= 30
       0 2486.36    29.6 2477.73  115.162472.342  147.432470.826  149.752470.707
   204.22468.327  218.932468.011   300.3 2463.38   329.3 2460.61  357.282456.154
   394.2 2453.93   407.2 2451.56   431.7 2451.84   441.7 2450.01     460  2451.7
  490.382452.623   506.62452.875  554.822452.885   582.52453.001  618.95 2451.07
   632.1 2449.55  651.012452.409   658.42452.926   749.6 2453.38  811.34 2458.66
   824.4 2461.36   838.2 2461.61   849.4  2464.3  875.47 2467.23   922.3 2474.41
#Mann= 18 ,-1 , 0
       0     .12       0  115.16     .06       0  147.43     .12       0
  149.75     .06       0   204.2     .12       0  218.93     .06       0
  357.28     .12       0   431.7    .045       0     460     .12       0
  490.38     .06       0   506.6     .12       0  554.82     .06       0
   582.5     .12       0  618.95     .06       0  651.01     .12       0
   658.4     .06       0  811.34    .016       0  875.47     .06       0
Bank Sta=431.7,460
XS Rating Curve= 0 ,0
Exp/Cntr=0.3,0.1

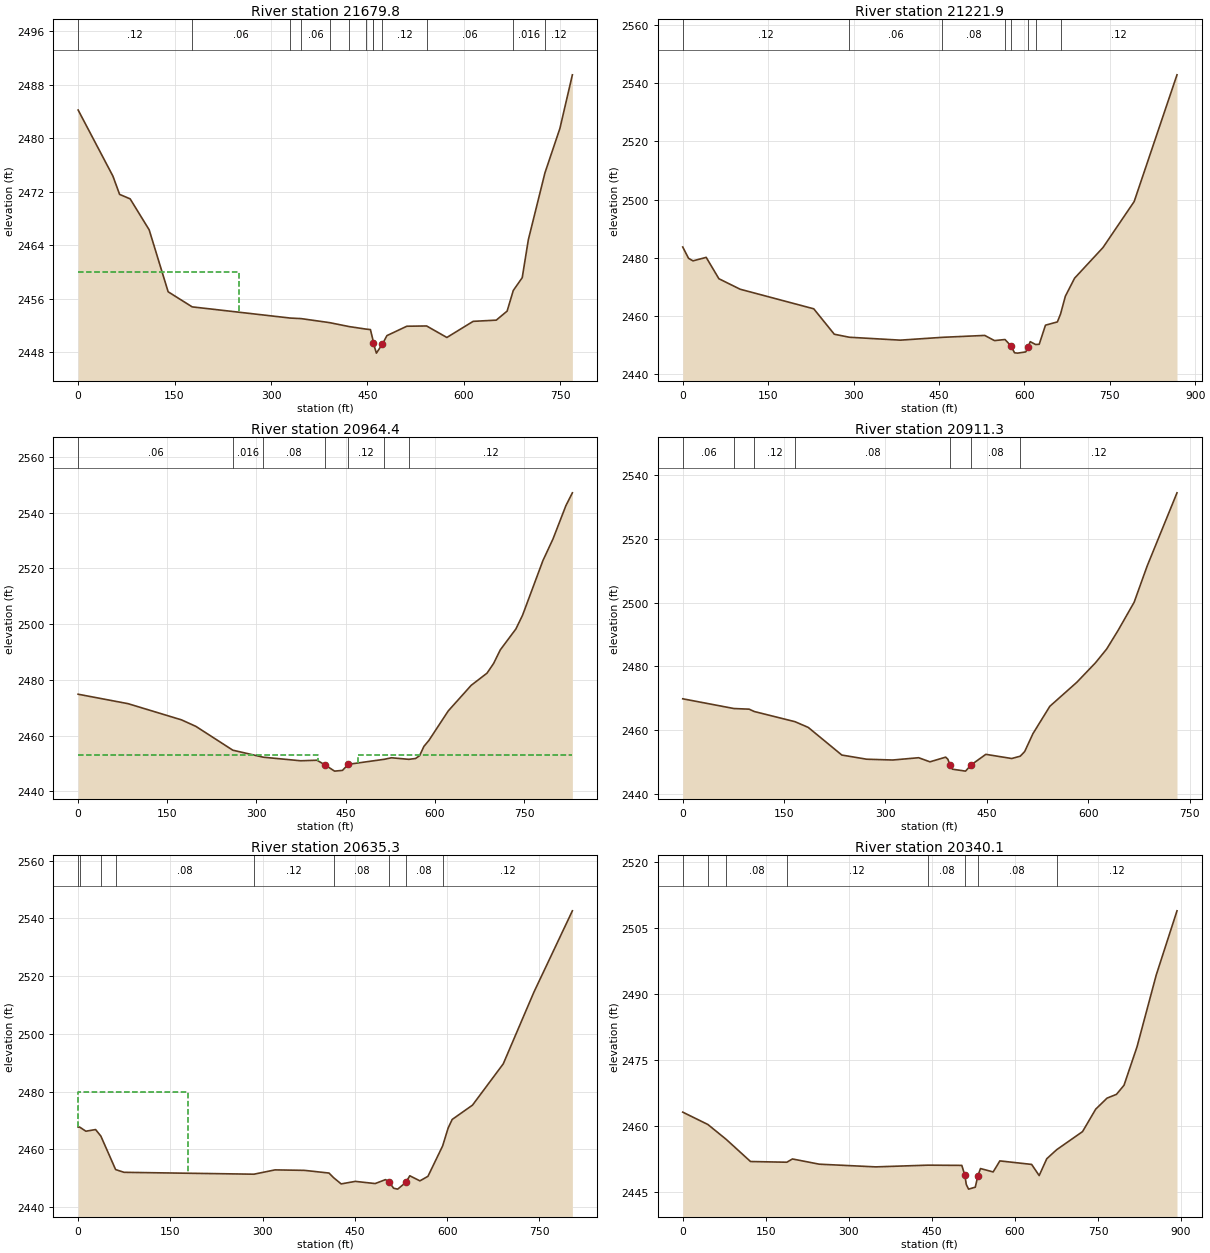
Type RM Length L Ch R = 1 ,21679.8 ,460.4,457.9,440
XS GIS Cut Line= 4
     2037541.383      335596.136     2037966.544      335708.021
     2038026.608      335772.796     2038219.756      335916.479
#Sta/Elev= 30
       0 2484.22    54.1 2474.34    64.5 2471.61    80.9 2470.94   110.5 2466.31
     140 2457.05  177.392454.794   330.1 2453.12  346.79 2453.04  391.192452.436
  421.732451.844  447.692451.473   454.6  2451.4   458.12450.017   459.2 2449.35
   463.9 2447.88   473.2 2449.23   480.3  2450.5   511.2  2451.9  541.972451.939
   573.5 2450.22   614.4 2452.63   650.3 2452.81   667.2 2454.16  676.792457.245
   690.7 2459.16   700.2 2464.83  726.042474.831   749.3 2481.47   768.7 2489.48
#Mann= 13 ,-1 , 0
       0     .12       0  177.39     .06       0   330.1     .12       0
  346.79     .06       0  391.19     .12       0  421.73     .06       0
  447.69     .12       0   458.1     .04       0   459.2    .045       0
   473.2     .12       0  541.97     .06       0  676.79    .016       0
  726.04     .12       0
#XS Ineff= 2 , 0
             250    2460
Permanent Ineff=
       F       F
Bank Sta=459.2,473.2
XS Rating Curve= 0 ,0
Exp/Cntr=0.3,0.1

Type RM Length L Ch R = 1 ,21221.9 ,260.2,257.4,117.4
XS GIS Cut Line= 4
      2037388.74      335716.841     2037872.408      335942.672
     2037929.454      336029.2392038103.66596557336180.449368601
#Sta/Elev= 30
       0 2483.65    10.2 2479.76      18 2478.88    41.2 2480.08    63.5 2472.72
   100.9  2469.1   230.1 2462.36   266.2  2453.6  292.592452.563   382.2 2451.56
  455.582452.529   530.4 2453.19   547.5 2451.41  566.042451.777   576.3  2449.6
   582.8  2447.2   588.2 2447.09   602.5 2447.51     607 2449.37   610.3 2451.04
  619.722450.061   626.1 2450.13   637.1 2456.72     658 2457.84  663.542460.542
     672 2466.68   688.2  2472.9   738.1 2483.46   792.9 2499.32   868.1 2542.97
#Mann= 8 ,-1 , 0
       0     .12       0  292.59     .06       0  455.58     .08       0
  566.04     .12       0   576.3    .045       0     607     .12       0
  619.72    .016       0  663.54     .12       0
Bank Sta=576.3,607
XS Rating Curve= 0 ,0
Exp/Cntr=0.5,0.3

Type RM Length L Ch R = 1 ,20964.4 ,54.6,53.1,91.7
XS GIS Cut Line= 5
2037314.09007609335935.934838762 2037628.9010363336039.881853925
2037686.81437332336075.5208305532037790.76138848336068.096043755
2038077.35815886 336226.98648122
#Sta/Elev= 30
       0 2474.88      84 2471.49   173.8 2465.69     198 2463.36   260.2 2454.81
   311.3  2452.3   374.4 2451.01   401.8 2451.21     415 2449.56   431.4  2447.3
   444.7 2447.57   454.4 2449.74     515 2451.54     527 2452.09   556.3 2451.53
   567.6 2451.83   574.4 2452.84   581.6 2456.15   590.1 2458.33   622.6 2468.89
   661.2 2478.07   687.8 2482.43   698.9 2485.91   710.1 2490.77   736.4 2498.29
   747.6 2503.21   781.9 2522.83   798.8 2530.56   820.5 2542.51   831.4  2547.1
#Mann= 7 ,-1 , 0
       0     .06       0   260.2    .016       0   311.3     .08       0
     415    .045       0   454.4     .12       0     515    .016       0
   556.3     .12       0
#XS Ineff= 2 , 0
          403.46  2453.2     471          2453.2
Permanent Ineff=
       F       F
Bank Sta=415,454.4
XS Rating Curve= 0 ,0
Exp/Cntr=0.5,0.3

Type RM Length L Ch R = 1 ,20911.3 ,277.3,276,283.7
XS GIS Cut Line= 4
     2037343.222      336053.413     2037714.444      336125.942
     2037809.212      336114.434     2038028.474      336249.757
#Sta/Elev= 30
       0 2469.85   75.742466.795    98.3 2466.59  105.832465.858  166.02 2462.67
   185.7 2460.87   235.4 2452.19   272.2 2450.88   310.8 2450.63   349.1 2451.35
   365.8 2450.06   389.1 2451.53   392.4 2450.84   395.7 2448.92     399 2447.75
   418.5 2447.14   426.7 2449.08   448.5 2452.41   486.8  2451.1  499.392451.823
     506 2453.28   518.2 2458.89   543.2 2467.49   583.1 2475.02   610.8 2481.16
   627.4  2485.5   644.2 2491.31     668 2500.17   687.2 2511.51   731.4 2534.52
#Mann= 7 ,-1 , 0
       0     .06       0   75.74    .016       0  105.83     .12       0
  166.02     .08       0   395.7    .045       0   426.7     .08       0
  499.39     .12       0
Bank Sta=395.7,426.7
XS Rating Curve= 0 ,0
Exp/Cntr=0.5,0.3

Type RM Length L Ch R = 1 ,20635.3 ,251.3,295.2,342.4
XS GIS Cut Line= 4
      2037267.94       336184.02     2037604.295      336391.726
     2037838.192       336395.73     2038009.744      336426.007
#Sta/Elev= 30
       0 2467.71    2.262467.761    12.6  2466.3    28.4 2466.87   36.982464.598
   60.972453.014    74.6 2452.07  285.842451.418   320.1 2452.91   367.8 2452.75
   407.9 2451.81  415.342450.205   427.6 2448.06   450.6 2448.93   482.9 2448.18
   499.8 2449.55   505.82448.634   512.9 2446.56   519.5 2446.25   532.6 2448.55
   539.2 2450.87   555.6 2449.11   568.7 2450.68  592.582461.207   601.5 2467.39
   608.1 2470.37   641.1 2475.32   691.1 2489.61     741 2514.46   803.5 2542.59
#Mann= 9 ,-1 , 0
       0     .12       0    2.26    .016       0   36.98     .12       0
   60.97     .08       0  285.84     .12       0  415.34     .08       0
   505.8    .045       0   532.6     .08       0  592.58     .12       0
#XS Ineff= 2 , 0
             178    2480
Permanent Ineff=
       F       F
Bank Sta=505.8,532.6
XS Rating Curve= 0 ,0
Exp/Cntr=0.3,0.1

Type RM Length L Ch R = 1 ,20340.1 ,353.3,348.8,186.1
XS GIS Cut Line= 4
     2037140.775      336367.369     2037569.354      336584.575
     2037637.206      336678.975     2037922.452      336757.666
#Sta/Elev= 30
       0 2463.19   45.382460.384   78.492456.998   122.4 2451.96  187.992451.799
   198.1 2452.54   246.8 2451.35   348.6 2450.74  442.742451.132     504 2451.08
   509.5 2448.82   512.1 2446.73   516.2 2445.68   528.3 2446.12     533 2448.71
   537.7 2450.36   560.6 2449.59   572.7  2452.1   630.1  2451.3   643.7 2448.77
   657.4 2452.59  675.272454.645     722 2458.76   745.8 2463.87   766.3 2466.38
   783.3 2467.24   796.9  2469.3   820.5 2478.09   855.1 2494.38   892.6 2508.98
#Mann= 8 ,-1 , 0
       0     .12       0   45.38    .016       0   78.49     .08       0
  187.99     .12       0  442.74     .08       0   509.5    .045       0
     533     .08       0  675.27     .12       0
Bank Sta=509.5,533
XS Rating Curve= 0 ,0
Exp/Cntr=0.3,0.1

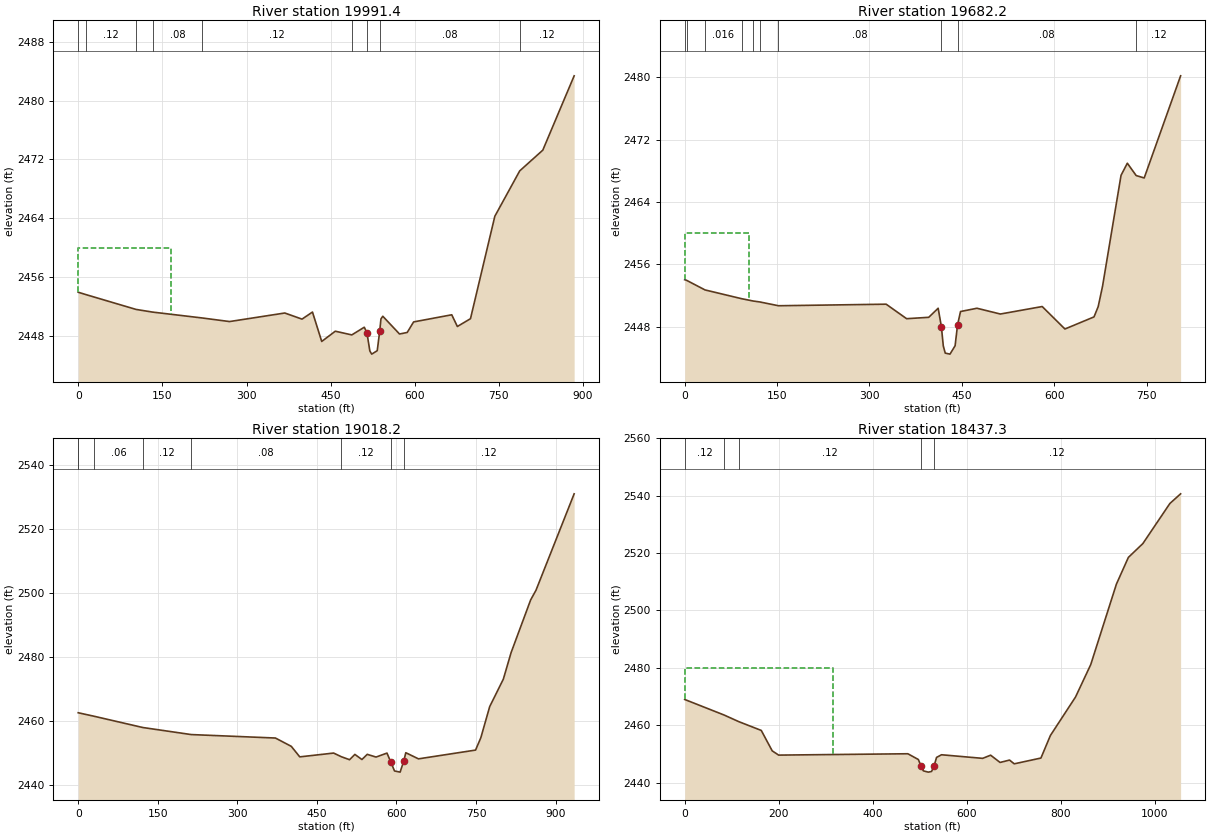
Type RM Length L Ch R = 1 ,19991.4 ,241.1,309.1,255.1
XS GIS Cut Line= 4
      2036960.18      336761.048     2037358.913      336775.359
     2037566.542      336752.256     2037837.763      336804.596
#Sta/Elev= 30
       0 2453.98   14.312453.646  102.982451.649  132.542451.285  221.212450.485
   269.8    2450   368.3 2451.16     399 2450.33   417.6 2451.29   434.1  2447.3
   458.3 2448.69   487.72448.188     510 2449.23   514.7 2448.47   519.9 2446.01
   523.2 2445.58   533.1 2446.05   537.52448.723   539.7 2450.36     543 2450.72
   572.8 2448.31   586.5 2448.52   597.9 2449.95   665.9 2450.92   675.9 2449.33
   699.3 2450.39   742.7 2464.29  787.06 2470.45   828.2 2473.26   884.1 2483.35
#Mann= 9 ,-1 , 0
       0     .06       0   14.31     .12       0  102.98    .016       0
  132.54     .08       0  221.21     .12       0   487.7     .08       0
   514.7    .045       0   537.5     .08       0  787.06     .12       0
#XS Ineff= 2 , 0
             165    2460
Permanent Ineff=
       F       F
Bank Sta=514.7,537.5
XS Rating Curve= 0 ,0
Exp/Cntr=0.3,0.1

Type RM Length L Ch R = 1 ,19682.2 ,464.8,664,498.8
XS GIS Cut Line= 4
     2037030.438      336880.022     2037426.906      336935.167
     2037482.767      336969.127     2037812.491        336888.6
#Sta/Elev= 30
       0 2454.05    3.152453.968   32.97 2452.74   92.612451.612  111.682451.311
  122.432451.191  152.262450.711   327.1 2450.91   360.3 2449.05   396.2 2449.23
   411.5 2450.39   416.7 2448.05  419.84 2445.56     423 2444.64   430.7 2444.51
     439 2445.58     443 2448.26   447.8 2449.97   474.5 2450.39   512.5 2449.65
   580.4 2450.61   617.3 2447.73   664.5 2449.28   671.3  2450.6   678.4 2453.23
   708.4 2467.43   718.6 2468.98  732.972467.396     746 2467.09   805.1 2480.18
#Mann= 10 ,-1 , 0
       0     .12       0    3.15     .06       0   32.97    .016       0
   92.61     .06       0  111.68     .12       0  122.43     .06       0
  152.26     .08       0   416.7    .045       0     443     .08       0
  732.97     .12       0
#XS Ineff= 2 , 0
             105    2460
Permanent Ineff=
       F       F
Bank Sta=416.7,443
XS Rating Curve= 0 ,0
Exp/Cntr=0.3,0.1

Type RM Length L Ch R = 1 ,19018.2 ,399,580.9,412.7
XS GIS Cut Line= 4
2036882.95401231337175.880298484     2037445.838       337271.85
     2037497.757      337292.715     2037798.702      337358.341
#Sta/Elev= 30
       0 2462.63      .32462.621   30.69 2461.51  121.862458.013  213.032455.812
   371.8 2454.73   401.7 2452.13   417.7 2448.84   481.6 2450.03   495.82448.903
   511.6 2447.95   521.6 2449.61   534.9 2448.01   544.9 2449.63   561.5 2448.78
   582.1 2450.02   589.2 2447.29   596.3 2444.44   606.9 2444.07   613.9  2447.6
   617.6 2450.14   641.5 2448.22   749.1 2450.96     759 2454.79   775.8 2464.56
   801.5 2473.14   816.1 2481.42     853 2497.91   863.1 2500.94     935 2531.07
#Mann= 8 ,-1 , 0
       0     .06       0      .3    .016       0   30.69     .06       0
  121.86     .12       0  213.03     .08       0   495.8     .12       0
   589.2    .045       0   613.9     .12       0
Bank Sta=589.2,613.9
XS Rating Curve= 0 ,0
Exp/Cntr=0.3,0.1

Type RM Length L Ch R = 1 ,18437.3 ,272.8,415.2,332.5
XS GIS Cut Line= 4
2036790.30383765337472.033232471     2037256.441      337551.453
     2037340.354      337518.8042037823.03762729337613.942806065
#Sta/Elev= 30
       0 2468.98   84.042463.546  115.052461.251   162.9 2458.19   186.2 2451.07
   199.9 2449.59   474.7 2450.06     497 2448.06   502.6 2445.87   507.6 2444.11
   518.2 2443.66   525.2 2443.89   530.5 2445.87   530.5 2445.89   535.8 2448.79
   546.3 2449.71   633.8 2448.46   650.8 2449.56   670.9 2447.03     691 2447.86
     701 2446.55   757.8 2448.57   777.9 2456.42   831.4 2469.84   863.7 2481.12
   918.3 2509.16   943.8 2518.48   974.6  2523.3    1032 2537.25  1054.9 2540.63
#Mann= 5 ,-1 , 0
       0     .12       0   84.04    .016       0  115.05     .12       0
   502.6    .045       0   530.5     .12       0
#XS Ineff= 2 , 0
             315    2480
Permanent Ineff=
       F       F
Bank Sta=502.6,530.5
XS Rating Curve= 0 ,0
Exp/Cntr=0.3,0.1