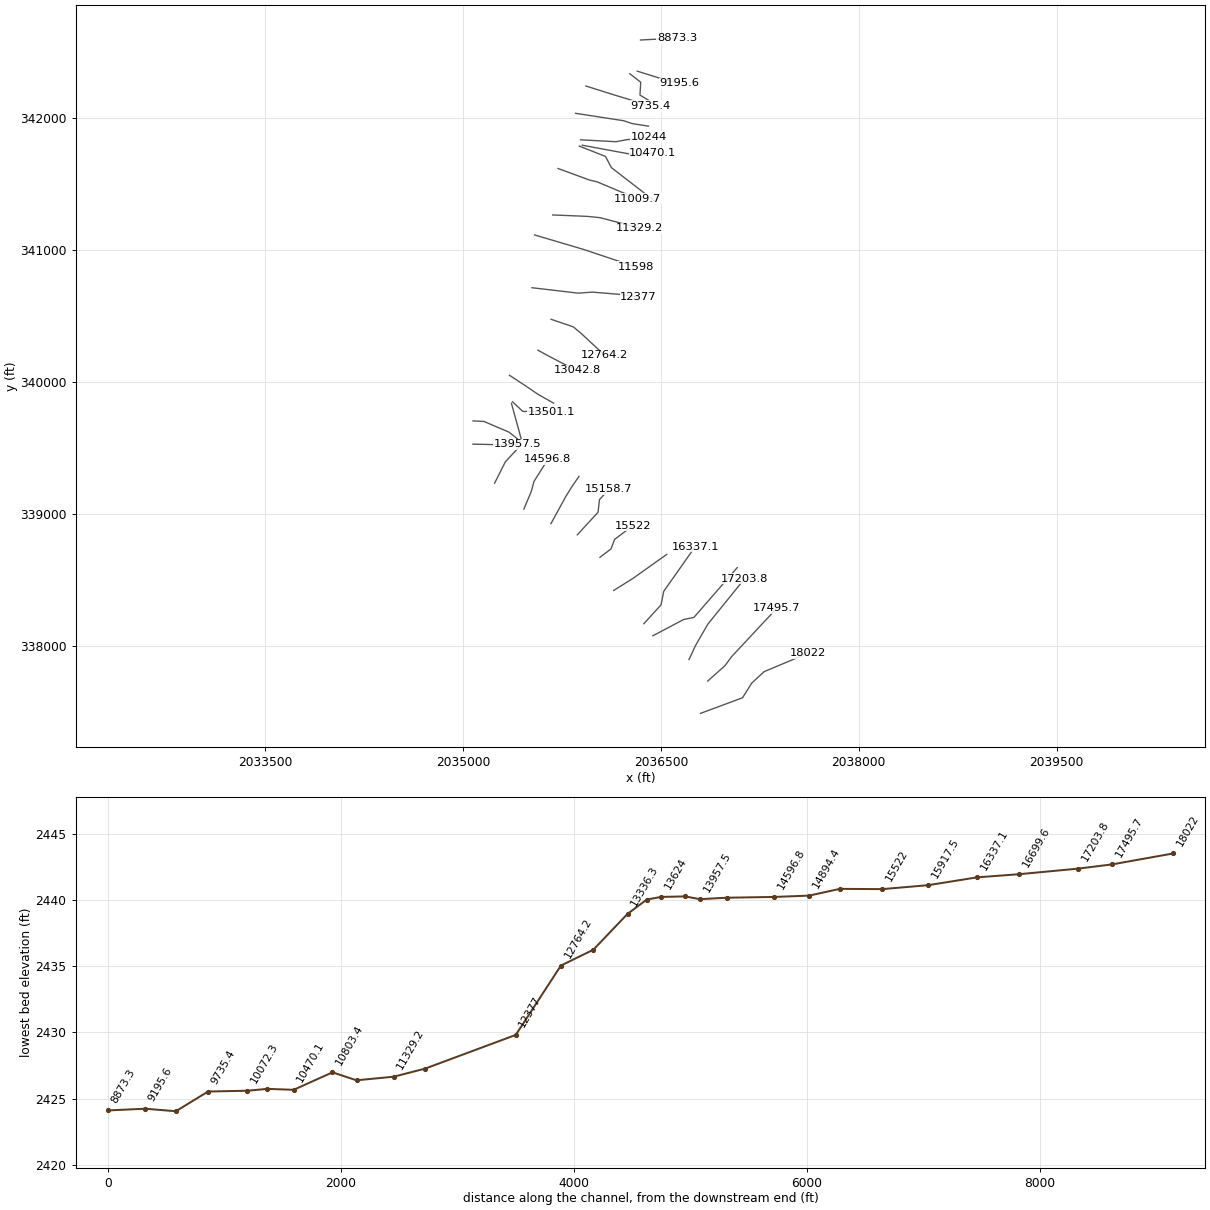
HEC-RAS study BOGGSCK.prj: BOGGSCK

--- BOGGSCK.g01 (geometry) --- (continued)

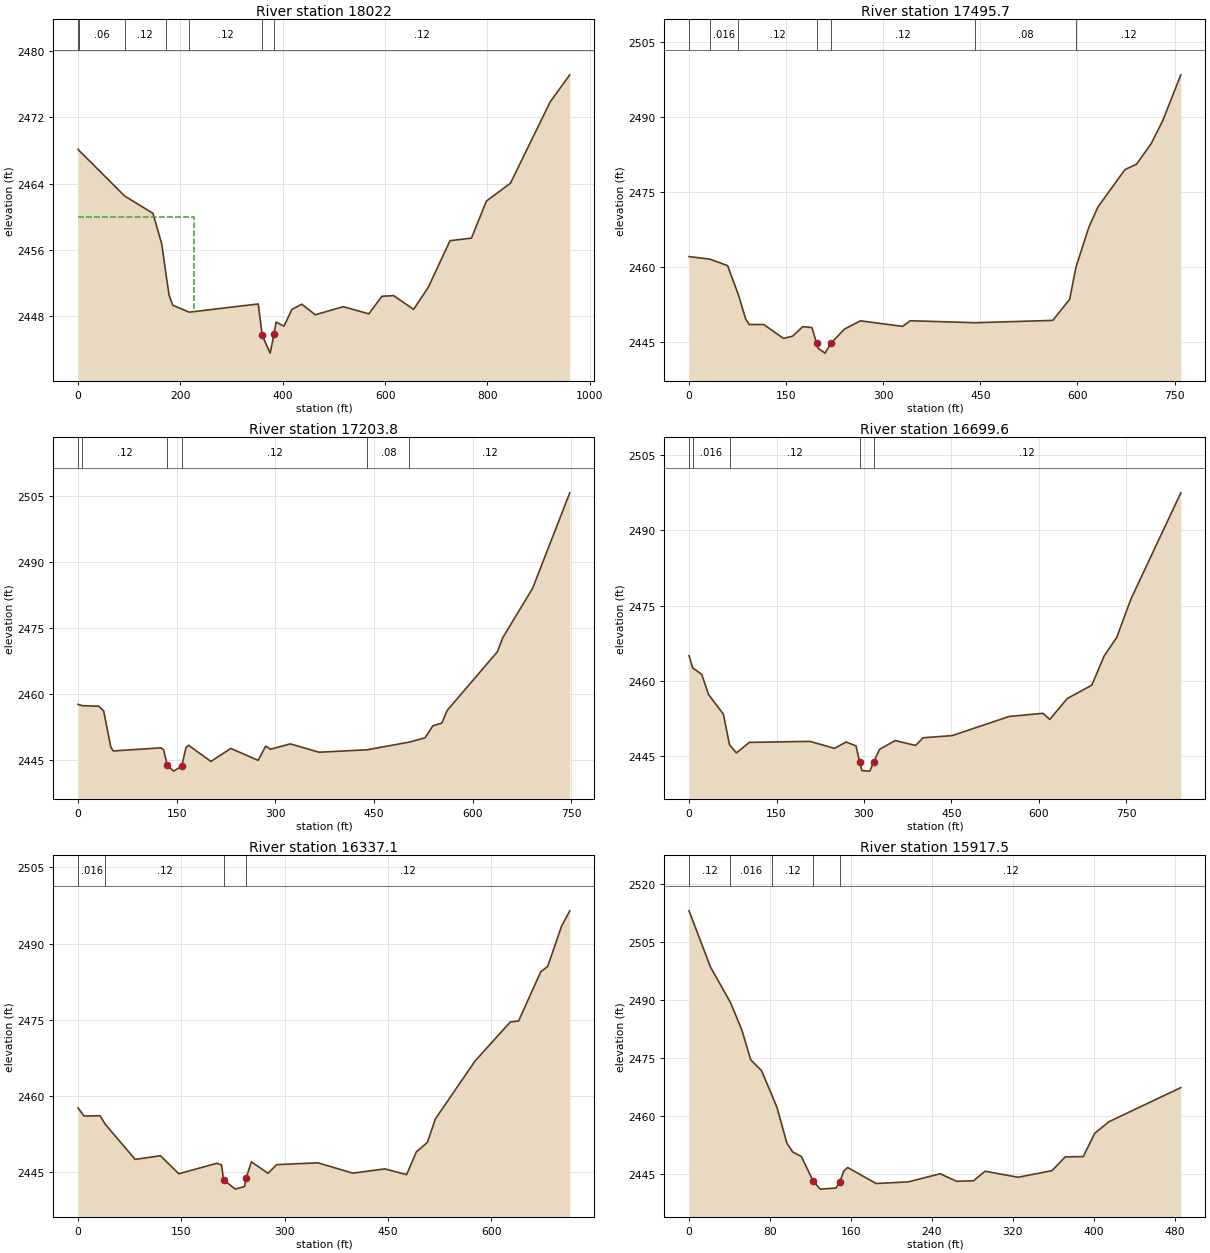
Type RM Length L Ch R = 1 ,18022   ,458.5,526.3,295.9
XS GIS Cut Line= 5
     2036800.411      337485.415     2037119.034      337603.707
     2037188.674       337715.32     2037283.116      337802.131
2037616.21161213337941.896356288
#Sta/Elev= 30
       0 2468.15    2.112467.997   91.152462.506   146.5 2460.41   163.7 2456.69
  171.842453.112     178 2450.52     185 2449.32  217.182448.475   352.2 2449.47
     360 2445.66   375.4 2443.53   383.22445.887     387 2447.27   402.5 2446.79
     418 2448.82   437.3 2449.44   463.6 2448.16   518.3 2449.14   568.3 2448.27
   593.8 2450.39   616.6 2450.48   655.7 2448.82   684.2 2451.45   726.9 2457.11
   768.8 2457.42     798 2461.89   845.1 2464.06   922.6 2473.87   960.9 2477.14
#Mann= 7 ,-1 , 0
       0     .12       0    2.11     .06       0   91.15     .12       0
  171.84    .016       0  217.18     .12       0     360    .045       0
   383.2     .12       0
#XS Ineff= 2 , 0
             226    2460
Permanent Ineff=
       F       F
Bank Sta=360,383.2
XS Rating Curve= 0 ,0
Exp/Cntr=0.3,0.1

Type RM Length L Ch R = 1 ,17495.7 ,326.2,291.9,337.6
XS GIS Cut Line= 4
     2036855.408      337730.567     2036985.147       337846.95
     2037040.477      337920.4052037377.28931365338281.075929883
#Sta/Elev= 30
       0 2462.01   32.072461.507    59.6  2460.2   76.312454.336    87.4 2449.56
      93 2448.42   115.3 2448.43   145.9 2445.65   159.8 2446.08   175.7    2448
   189.8 2447.82   196.92444.715   199.2 2443.69   210.1  2442.7   219.7 2444.76
   240.2 2447.52   264.8 2449.16   329.8 2448.05   341.7 2449.18  442.122448.784
   561.9 2449.25     588 2453.49  597.692459.896   617.6 2467.88   631.5 2471.91
   673.3 2479.41   691.2 2480.51   713.7 2484.57   731.4 2489.11   759.7 2498.38
#Mann= 7 ,-1 , 0
       0     .12       0   32.07    .016       0   76.31     .12       0
   196.9    .045       0   219.7     .12       0  442.12     .08       0
  597.69     .12       0
Bank Sta=196.9,219.7
XS Rating Curve= 0 ,0
Exp/Cntr=0.3,0.1

Type RM Length L Ch R = 1 ,17203.8 ,361.9,504.3,444.2
XS GIS Cut Line= 4
     2036713.268      337893.694      2036761.92       337998.63
     2036856.362      338162.7122037134.98331365338507.075247634
#Sta/Elev= 30
       0 2457.58    6.582457.287    31.9 2457.16    39.1 2456.06    49.9 2447.87
    53.6 2446.97   126.3 2447.69   130.1 2447.23   135.9  2443.7   145.5 2442.38
   157.82443.525   164.2 2447.73     168 2448.28   202.1  2444.6   232.4 2447.55
     274 2444.83   285.4 2448.08   292.9 2447.37   322.8 2448.59   366.6 2446.68
  440.262447.256  504.062448.994   527.9 2449.97   539.7 2452.72   553.2  2453.3
   561.6 2456.23   637.9 2469.59     646 2472.78   691.4 2484.03   747.9 2505.77
#Mann= 6 ,-1 , 0
       0     .06       0    6.58     .12       0   135.9    .045       0
   157.8     .12       0  440.26     .08       0  504.06     .12       0
Bank Sta=135.9,157.8
XS Rating Curve= 0 ,0
Exp/Cntr=0.3,0.1

Type RM Length L Ch R = 1 ,16699.6 ,286.6,362.5,331.4
XS GIS Cut Line= 4
     2036439.481      338073.993     2036672.248      338197.054
     2036750.473      338213.2722037078.72716235338590.835266902
#Sta/Elev= 30
       0    2465    6.192462.585    21.8 2461.27    33.3 2457.28    58.9 2453.33
   69.392447.241    81.2  2445.6   103.5  2447.7   207.4  2447.9   249.4 2446.51
   269.6 2447.78   286.5 2446.99   292.42443.796   296.6 2442.05     310 2441.96
   316.5 2443.75   326.7  2446.3   353.5 2448.06   388.5 2447.09   401.5 2448.62
   451.3 2449.05     549 2452.87   607.1  2453.5   618.7 2452.28   648.7 2456.45
   690.8 2459.12   711.8 2464.91   733.7 2468.69   757.9 2476.32   843.5 2497.52
#Mann= 5 ,-1 , 0
       0     .12       0    6.19    .016       0   69.39     .12       0
   292.4    .045       0   316.5     .12       0
Bank Sta=292.4,316.5
XS Rating Curve= 0 ,0
Exp/Cntr=0.3,0.1

Type RM Length L Ch R = 1 ,16337.1 ,355,419.6,334.4
XS GIS Cut Line= 4
     2036370.796      338165.574     2036501.488      338308.668
     2036521.522      338410.7422036760.90416646338751.073418196
#Sta/Elev= 30
       0 2457.71     8.8  2456.1      32 2456.16    39.92454.421      83 2447.57
   119.7 2448.29   146.4 2444.74   201.6 2446.81   208.3  2446.5  211.312443.571
   228.2 2441.72   241.7 2442.23   244.22443.954   251.7 2447.09   275.7 2444.84
   288.5 2446.54   348.4 2446.89     399 2444.86   445.4  2445.7     477 2444.57
   491.1 2449.03   507.3 2450.93   518.7 2455.51   576.5 2466.94   627.6  2474.6
   639.6 2474.79   671.7 2484.45   681.9 2485.54     702 2493.44   713.9 2496.46
#Mann= 4 ,-1 , 0
       0    .016       0    39.9     .12       0  211.31    .045       0
   244.2     .12       0
Bank Sta=211.31,244.2
XS Rating Curve= 0 ,0
Exp/Cntr=0.3,0.1

Type RM Length L Ch R = 1 ,15917.5 ,366.1,395.5,426.8
XS GIS Cut Line= 3
     2036142.269       338417.42     2036287.483      338508.576
     2036543.993      338690.889
#Sta/Elev= 30
       0 2513.06    21.2 2498.52   40.952489.353    52.2 2482.26      61 2474.55
    71.6 2471.77   81.722465.536    87.1  2462.1    96.7 2453.03   102.5 2450.74
     111 2449.56   122.9 2443.12   129.7 2441.13   145.2  2441.4   149.2 2443.04
   152.9 2445.77   156.8 2446.72     185 2442.58   216.6    2443   248.2  2445.1
   264.6 2443.15   281.3 2443.29   292.6 2445.76   325.3  2444.2   358.8  2445.9
   371.9 2449.47   389.7 2449.54   401.1 2455.57   415.2 2458.56   486.2 2467.37
#Mann= 5 ,-1 , 0
       0     .12       0   40.95    .016       0   81.72     .12       0
   122.9    .045       0   149.2     .12       0
Bank Sta=122.9,149.2
XS Rating Curve= 0 ,0
Exp/Cntr=0.3,0.1

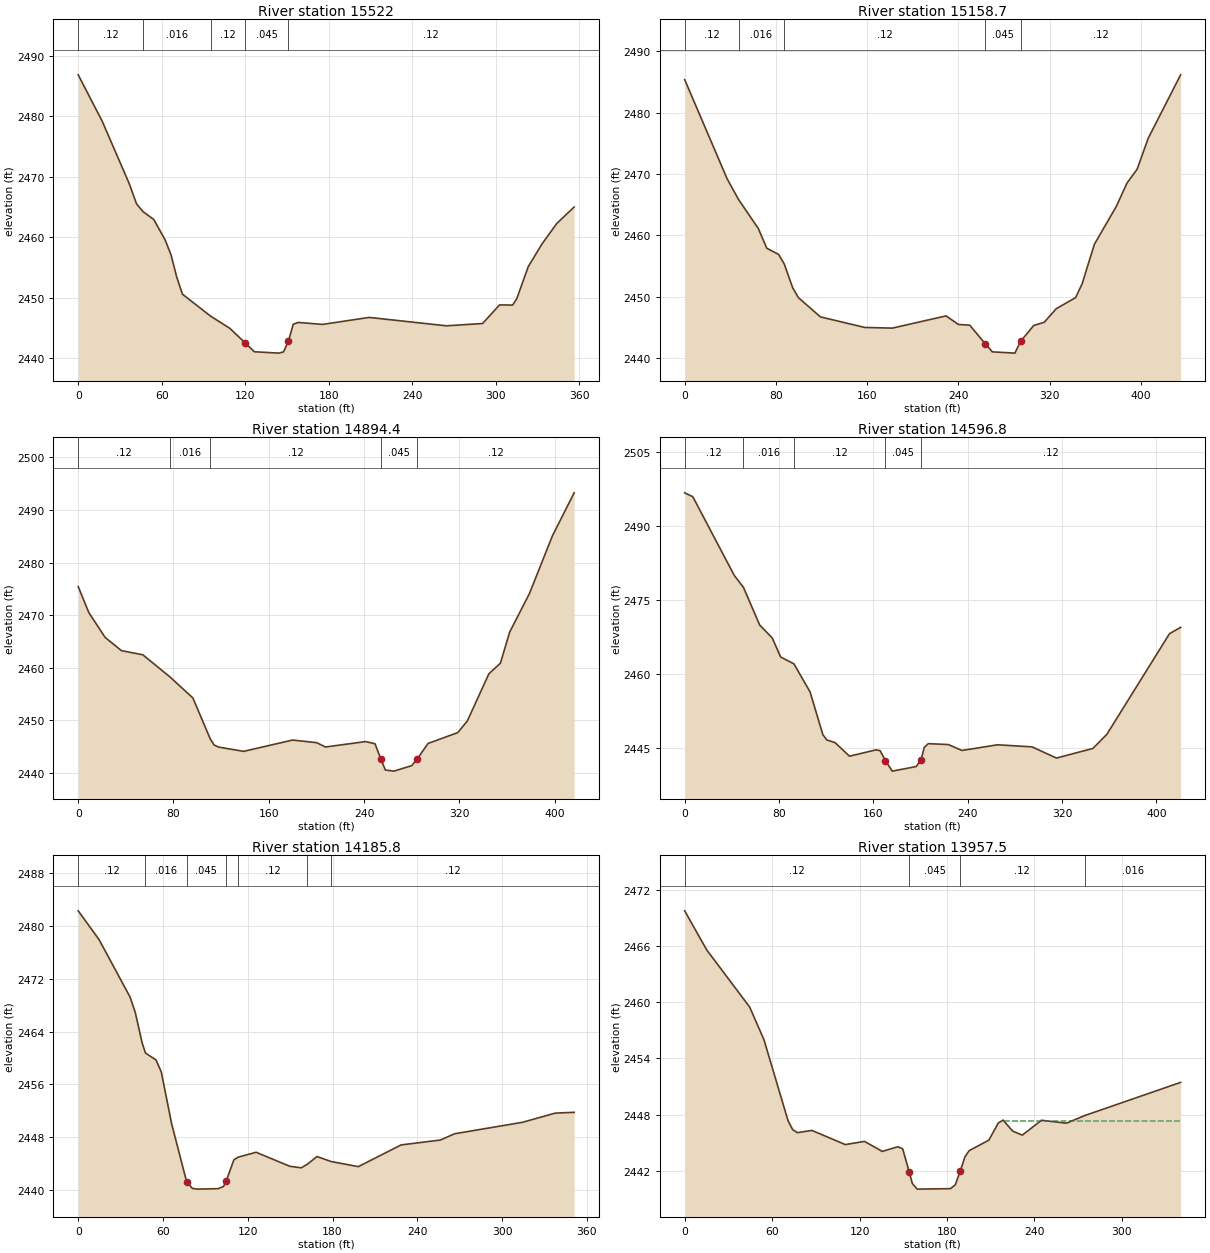
Type RM Length L Ch R = 1 ,15522   ,312.1,363.2,383.6
XS GIS Cut Line= 4
     2036038.333      338668.959     2036121.997      338732.835
      2036149.55      338805.226     2036288.302        338909.5
#Sta/Elev= 30
       0 2486.88    17.1 2479.27    36.7 2468.86    41.9 2465.53   46.482464.262
    54.3 2462.94    62.5 2459.54    66.7 2457.08    70.8 2453.39    74.9 2450.58
   95.152446.945   108.9 2444.94   119.7 2442.58   126.5 2441.06     144 2440.83
   147.5 2441.03     151  2442.8   154.5 2445.61   158.1 2445.91   175.5 2445.58
     209 2446.74   264.5 2445.35   290.5 2445.73   302.7 2448.81   312.1 2448.78
   315.1 2449.85   323.3 2455.13   333.2 2458.89   343.8 2462.28   356.3 2465.01
#Mann= 5 ,-1 , 0
       0     .12       0   46.48    .016       0   95.15     .12       0
   119.7    .045       0     151     .12       0
Bank Sta=119.7,151
XS Rating Curve= 0 ,0
Exp/Cntr=0.3,0.1

Type RM Length L Ch R = 1 ,15158.7 ,282.2,264.3,240
XS GIS Cut Line= 4
     2035866.546      338839.576      2036023.95      339011.289
     2036034.443      339106.685     2036106.945      339183.956
#Sta/Elev= 30
       0 2485.36    37.2 2469.23   47.222465.859    64.6 2461.12      72 2457.92
    82.4 2456.91   87.292455.365    94.7  2451.5    99.6  2449.9     119 2446.75
   157.9 2445.03   182.1 2444.92   229.2 2446.91   240.1 2445.51     250  2445.4
   263.42442.411   269.8 2441.06   289.6 2440.85   294.5 2442.75   306.1 2445.35
   315.3 2445.87   325.9 2448.09   342.8 2449.88   348.5 2452.11   359.3 2458.57
   378.5 2464.72   387.9 2468.53   396.8 2470.79   406.5 2475.82   434.9 2486.14
#Mann= 5 ,-1 , 0
       0     .12       0   47.22    .016       0   87.29     .12       0
   263.4    .045       0   294.5     .12       0
Bank Sta=263.4,294.5
XS Rating Curve= 0 ,0
Exp/Cntr=0.3,0.1

Type RM Length L Ch R = 1 ,14894.4 ,285,297.6,305.7
XS GIS Cut Line= 4
     2035667.092      338924.818     2035779.447      339130.429
     2035820.756      339197.312     2035878.981      339282.861
#Sta/Elev= 30
       0 2475.44     8.9  2470.5    22.6 2465.77    36.3 2463.26    54.3 2462.46
   77.162458.229    96.3 2454.25  110.822446.493   114.1 2445.31   117.9 2444.91
   138.9  2444.1     180 2446.25   200.3 2445.75   207.6 2444.93   241.3 2445.96
   249.2 2445.55     2542442.694   257.9 2440.55   265.1 2440.34     280 2441.38
   284.6 2442.64   293.7  2445.6   318.7 2447.67   326.7 2449.87   344.8 2458.85
   354.5 2460.88   362.3  2466.8   378.9 2474.13   398.1 2485.06   416.4 2493.27
#Mann= 5 ,-1 , 0
       0     .12       0   77.16    .016       0  110.82     .12       0
     254    .045       0   284.6     .12       0
Bank Sta=254,284.6
XS Rating Curve= 0 ,0
Exp/Cntr=0.3,0.1

Type RM Length L Ch R = 1 ,14596.8 ,318.1,411,389
XS GIS Cut Line= 4
     2035461.845      339035.159     2035517.493      339168.258
     2035538.383       339245.01     2035643.601      339411.274
#Sta/Elev= 30
       0 2496.68     6.9 2495.89      42 2479.95   49.842477.512    63.6 2469.88
    74.3 2467.23    81.4 2463.38   92.662462.001   106.3 2456.33   117.2 2447.63
   120.5 2446.58   127.6 2446.01   139.8 2443.27   162.4 2444.56   165.8 2444.38
  170.22 2442.39     176 2440.24   196.4 2441.17  200.52 2442.57   203.2 2445.05
   206.6 2445.81   223.6 2445.63   235.2 2444.43   265.3 2445.58   294.6 2445.16
   315.3 2442.89   346.2 2444.84   358.1 2447.72   411.2 2468.12   420.6 2469.39
#Mann= 5 ,-1 , 0
       0     .12       0   49.84    .016       0   92.66     .12       0
  170.22    .045       0  200.52     .12       0
Bank Sta=170.22,200.52
XS Rating Curve= 0 ,0
Exp/Cntr=0.3,0.1

Type RM Length L Ch R = 1 ,14185.8 ,289.5,228.3,166.4
XS GIS Cut Line= 3
     2035239.899      339231.654     2035321.516      339393.828
     2035437.051      339517.843
#Sta/Elev= 30
       0 2482.25    14.7 2477.92    36.7 2469.22    40.4 2466.88    45.2 2462.33
   47.582460.763    55.1  2459.7    58.8 2457.89    66.1 2450.08    76.7 2441.32
    80.8 2440.29    84.5 2440.18      99 2440.25   102.8 2440.57   104.72441.386
   110.2 2444.62  113.28 2445.02   125.9 2445.75   149.7 2443.64   157.9  2443.4
  162.17 2443.94     169 2445.11  178.982444.352   198.3 2443.58   228.5 2446.86
   256.3  2447.6   266.4 2448.55   314.4 2450.28   337.6 2451.67     351 2451.79
#Mann= 7 ,-1 , 0
       0     .12       0   47.58    .016       0    76.7    .045       0
   104.7    .016       0  113.28     .12       0  162.17    .016       0
  178.98     .12       0
Bank Sta=76.7,104.7
XS Rating Curve= 0 ,0
Exp/Cntr=0.3,0.1

Type RM Length L Ch R = 1 ,13957.5 ,149.9,127.4,106.7
XS GIS Cut Line= 3
     2035075.605      339527.382     2035319.425      339522.271
     2035415.841      339525.102
#Sta/Elev= 30
       0 2469.74    15.1 2465.58    44.6 2459.48    54.4    2456    70.9 2447.38
    74.1 2446.41    77.4 2446.09    87.3 2446.33   110.2 2444.82   123.4 2445.16
   135.6 2444.09   146.3 2444.59   149.6 2444.36  154.06 2441.92   156.2 2440.68
   159.5 2440.07   182.4 2440.12   185.7 2440.54     189 2441.95   192.3 2443.51
   195.2 2444.17   208.7 2445.29   215.2 2447.12   218.5 2447.43   225.1 2446.25
   231.7 2445.83   244.8 2447.41     262  2447.1  274.362447.904   340.3 2451.45
#Mann= 4 ,-1 , 0
       0     .12       0  154.06    .045       0     189     .12       0
  274.36    .016       0
#XS Ineff= 2 , 0
                          219.02         2447.35
Permanent Ineff=
       F       F
Bank Sta=154.06,189
XS Rating Curve= 0 ,0
Exp/Cntr=0.3,0.1

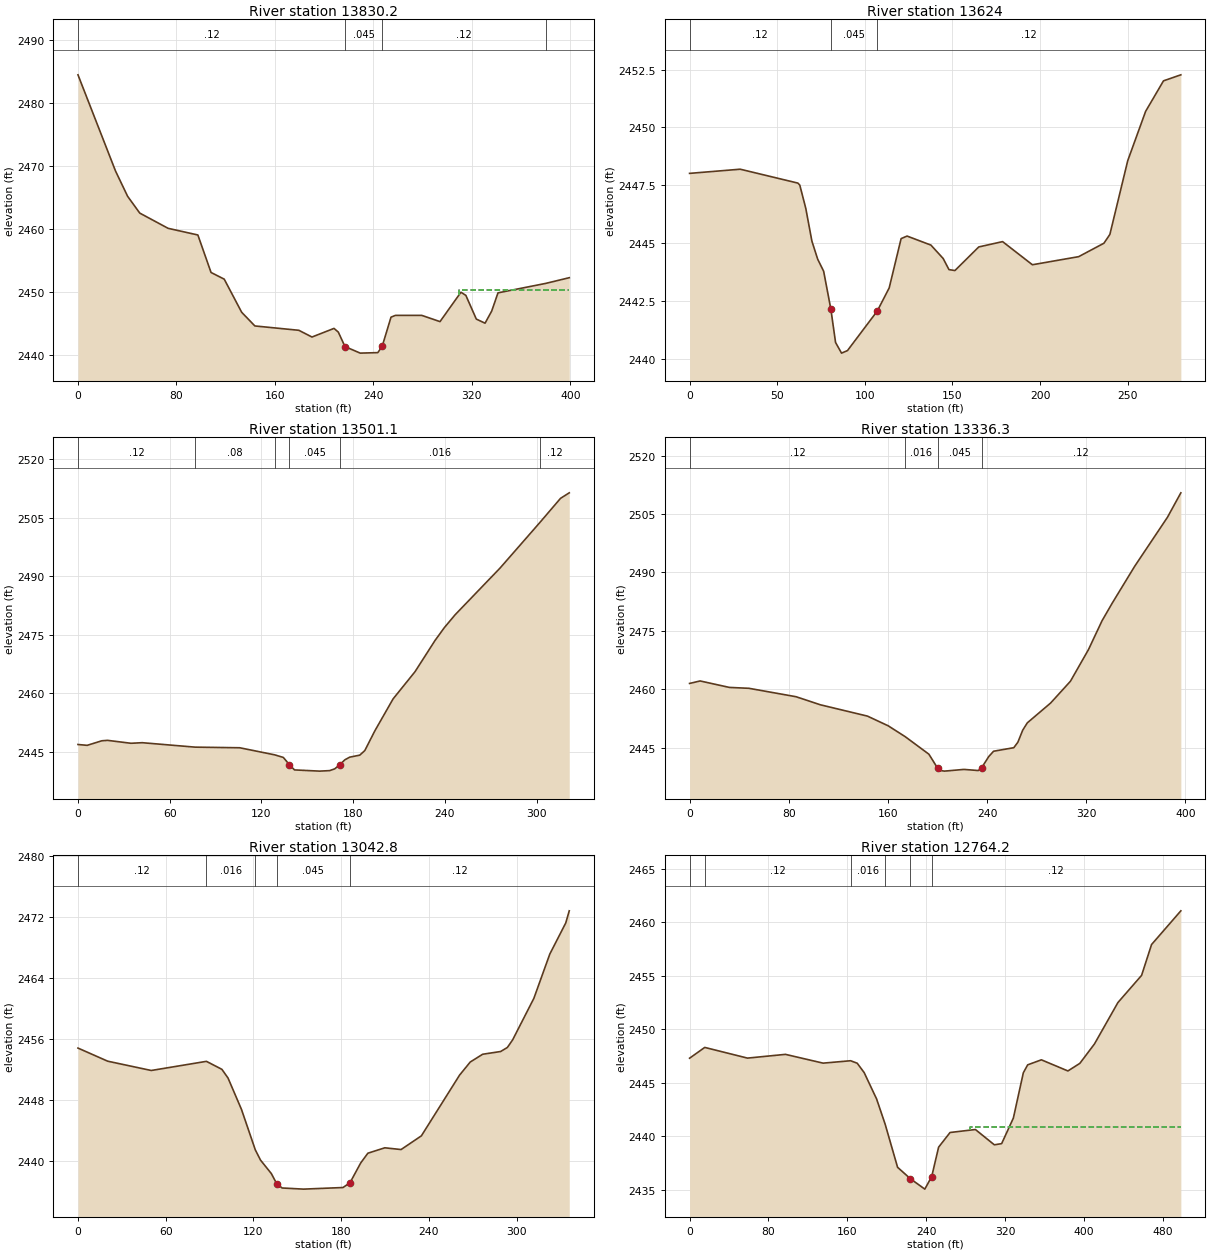
Type RM Length L Ch R = 1 ,13830.2 ,253.1,206.2,144.5
XS GIS Cut Line= 5
2035076.63274549339703.8372705692035159.14952098339699.428441096
2035349.55106622339618.0699839472035400.26679365339577.683468896
2035434.18320635339548.804236455
#Sta/Elev= 30
       0 2484.52    30.5 2469.23    40.3 2465.22    50.2 2462.54    73.2 2460.12
    97.4 2459.06   108.1  2453.1   118.8 2452.04     133 2446.77   143.7  2444.6
   179.4 2443.91   190.1 2442.84     208 2444.21   211.5 2443.62   216.9 2441.32
   229.3 2440.28   243.6 2440.36   247.2  2441.4   254.3    2446   257.9 2446.28
   279.3 2446.28   294.1 2445.29   311.1 2449.96   315.1 2449.46   323.6 2445.69
   330.7 2445.04   336.1 2446.97   341.2 2449.86  379.982451.364   399.1 2452.27
#Mann= 4 ,-1 , 0
       0     .12       0   216.9    .045       0   247.2     .12       0
  379.98    .016       0
#XS Ineff= 2 , 0
                           309.6          2450.3
Permanent Ineff=
       F       F
Bank Sta=216.9,247.2
XS Rating Curve= 0 ,0
Exp/Cntr=0.3,0.1

Type RM Length L Ch R = 1 ,13624   ,47.2,122.9,193.5
XS GIS Cut Line= 2
2035367.31097781339836.9178221182035441.55884578339566.655582693
#Sta/Elev= 30
       0 2448.01    28.9 2448.19    61.8 2447.59    62.9  2447.5    66.3  2446.5
    69.8 2445.08    73.1  2444.3    76.5 2443.78    80.62442.146    83.3  2440.7
    86.7 2440.24    90.1 2440.35   107.1 2442.06   113.9 2443.06   120.7 2445.19
   124.1  2445.3   137.7 2444.91   144.7 2444.33     148 2443.85   151.4 2443.81
     165 2444.83   178.6 2445.06   195.6 2444.06     222 2444.41   236.4 2444.99
   239.8 2445.37     250 2448.56   260.2 2450.69   270.4 2452.01   280.3 2452.27
#Mann= 3 , 0 , 0
       0     .12       0    80.6    .045       0   107.1     .12       0
Bank Sta=80.6,107.1
XS Rating Curve= 0 ,0
Exp/Cntr=0.3,0.1

Type RM Length L Ch R = 1 ,13501.1 ,189.1,164.8,134.8
XS GIS Cut Line= 4
2035375.07346551339849.285366412 2035452.9392485339776.014735452
 2035639.7925893  339772.44903012035667.23232274339770.578314716
#Sta/Elev= 30
       0 2446.87       6 2446.65    15.6 2447.82    19.4 2447.93    34.7 2447.18
      42 2447.33    76.6 2446.19   105.8 2446.03   128.6 2444.22   134.3 2443.55
   138.32441.681   141.6 2440.35     158 2440.04   164.6 2440.17   167.9 2440.62
   171.2 2441.68   174.5 2442.93   177.7 2443.62   184.3 2444.14   187.6 2445.32
   194.1 2450.33   206.1 2458.57   220.4 2465.52   233.5 2473.53   239.6 2476.83
   246.6 2480.11     276 2492.09     3022503.755   315.6 2509.99   321.3  2511.4
#Mann= 6 ,-1 , 0
       0     .12       0    76.6     .08       0   128.6    .016       0
   138.3    .045       0   171.2    .016       0     302     .12       0
Bank Sta=138.3,171.2
XS Rating Curve= 0 ,0
Exp/Cntr=0.3,0.1

Type RM Length L Ch R = 1 ,13336.3 ,287.2,293.5,299.1
XS GIS Cut Line= 4
     2035352.535      340049.889      2035466.73      339974.685
     2035568.802       339905.31     2035687.303      339838.116
#Sta/Elev= 30
       0 2461.49     8.5 2462.13    32.1 2460.47    47.9 2460.24    85.9 2458.08
   105.6    2456   143.5  2453.1   160.3  2450.6  174.032447.804   193.1 2443.31
   200.2 2439.69   201.7 2439.14   205.7 2438.96   221.4  2439.4   232.9 2439.11
   235.6 2439.79   241.4  2442.7   245.3 2444.07   261.6 2444.98   264.9 2446.39
   268.8 2449.48   272.5 2451.36   291.3 2456.45   307.3 2462.05   321.8 2470.15
   332.8 2477.59     341 2482.11   359.2 2491.62   385.6 2504.19   396.4 2510.47
#Mann= 4 ,-1 , 0
       0     .12       0  174.03    .016       0   200.2    .045       0
   235.6     .12       0
Bank Sta=200.2,235.6
XS Rating Curve= 0 ,0
Exp/Cntr=0.3,0.1

Type RM Length L Ch R = 1 ,13042.8 ,290.1,278.6,265.6
XS GIS Cut Line= 4
     2035568.305      340239.945     2035652.538      340193.613
     2035769.878      340132.619     2035867.164      340086.806
#Sta/Elev= 30
       0 2454.75    20.3 2453.03    50.1 2451.81   87.832453.009    98.4 2451.96
   102.6 2450.82   111.8  2446.7  121.222441.411   124.8 2440.06   132.2 2438.29
   135.9 2436.95   139.6  2436.4   154.2 2436.25   181.2 2436.46     186 2437.09
   193.3 2439.68   198.2 2440.96   209.8 2441.67   220.9 2441.44   234.8 2443.24
   260.9  2451.2   268.2 2452.92   276.7 2453.94     289  2454.3   293.6 2454.83
   297.2 2455.83   311.7 2461.27   322.6 2467.08   333.5 2471.16   335.9 2472.75
#Mann= 5 ,-1 , 0
       0     .12       0   87.83    .016       0  121.22     .12       0
   135.9    .045       0     186     .12       0
Bank Sta=135.9,186
XS Rating Curve= 0 ,0
Exp/Cntr=0.3,0.1

Type RM Length L Ch R = 1 ,12764.2 ,353.8,387.2,421.5
XS GIS Cut Line= 4
      2035667.94      340474.362     2035836.729      340416.804
     2035896.612       340366.49     2036073.444      340201.943
#Sta/Elev= 30
       0 2447.28   15.392448.289    58.7 2447.29    97.2 2447.64   135.4 2446.82
  163.282447.045     170 2446.81     177 2445.94   189.6 2443.48   198.32441.115
   210.9 2437.09   223.92436.021   238.5 2435.05   245.5 2436.22   252.5 2438.97
   264.1 2440.34   289.8 2440.62     309 2439.19   316.4  2439.3   328.3 2441.69
   338.4 2445.92   342.8 2446.66   356.7 2447.13   383.6 2446.09   395.7  2446.8
   410.5 2448.61   434.3 2452.48   458.3 2455.02   468.4  2457.9   498.1 2461.05
#Mann= 6 ,-1 , 0
       0     .07       0   15.39     .12       0  163.28    .016       0
   198.3     .12       0   223.9    .045       0   245.5     .12       0
#XS Ineff= 2 , 0
                          283.98         2440.88
Permanent Ineff=
       F       F
Bank Sta=223.9,245.5
XS Rating Curve= 0 ,0
Exp/Cntr=0.3,0.1

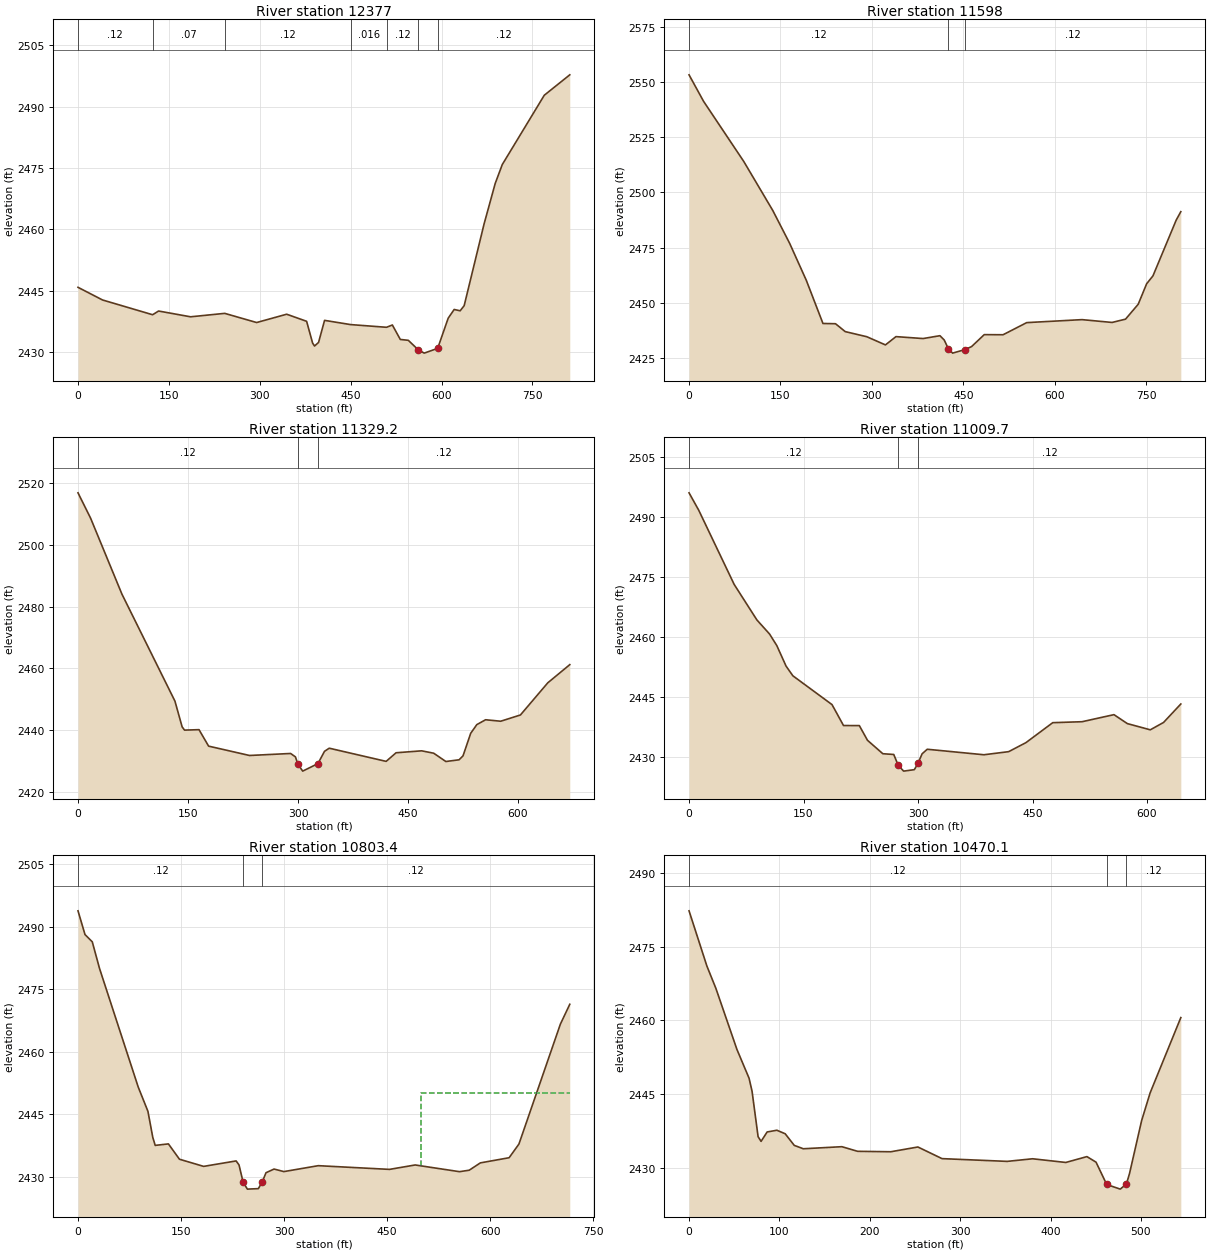
Type RM Length L Ch R = 1 ,12377   ,735.3,779,735.6
XS GIS Cut Line= 5
     2035522.939      340713.818     2035872.241      340672.717
     2035981.397       340680.42     2036179.417      340664.131
      2036330.01      340644.993
#Sta/Elev= 30
       0 2445.88    40.5 2442.79  123.162439.183     133 2440.09   185.8 2438.68
  242.12 2439.52   294.8 2437.28   344.4 2439.31   377.3 2437.58   387.2 2432.25
   390.4 2431.55     397 2432.42   406.9 2437.81  449.872436.779  509.14 2436.12
   518.8 2436.68   531.9 2433.15   545.1 2432.94   561.6 2430.61   571.4 2429.81
   593.6 2430.98   610.9 2438.33   620.8 2440.47   630.7 2440.15   637.3  2441.4
   670.2 2461.38   688.5 2471.23   700.2 2475.86   769.5 2492.78   811.6 2497.77
#Mann= 7 ,-1 , 0
       0     .12       0  123.16     .07       0  242.12     .12       0
  449.87    .016       0  509.14     .12       0   561.6    .045       0
   593.6     .12       0
#XS Ineff= 2 , 0
          414.36 2437.59
Permanent Ineff=
       F       F
Bank Sta=561.6,593.6
XS Rating Curve= 0 ,0
Exp/Cntr=0.3,0.1

Type RM Length L Ch R = 1 ,11598   ,256.8,268.8,279.6
XS GIS Cut Line= 4
     2035542.702      341114.225     2035909.962      341005.581
     2036032.506      340964.629     2036311.785      340870.944
#Sta/Elev= 30
       0 2553.24    23.8 2541.26    89.9 2513.97   137.4 2491.82     165 2476.99
   192.4 2460.21   219.7 2440.68   240.3 2440.57   256.2    2437   291.6 2434.69
   322.2 2430.98   339.5 2434.73     384 2433.86   411.6 2435.15   418.6 2433.21
   425.5  2429.2   432.4 2427.26   453.1  2428.9   463.5 2430.22   484.3 2435.63
   515.2 2435.58     554 2441.07   644.7 2442.42     694 2441.15   716.1 2442.64
   736.9 2449.39   750.7 2458.65   761.1 2462.24   799.2 2487.46   806.8 2491.29
#Mann= 3 ,-1 , 0
       0     .12       0   425.5    .045       0   453.1     .12       0
Bank Sta=425.5,453.1
XS Rating Curve= 0 ,0
Exp/Cntr=0.3,0.1

Type RM Length L Ch R = 1 ,11329.2 ,330,319.4,303.9
XS GIS Cut Line= 4
     2035680.412        341265.7     2035942.772      341254.899
     2036039.184      341245.094     2036340.129      341166.224
#Sta/Elev= 30
       0 2516.85    17.2 2508.62    59.9 2484.02   132.2 2449.33     142 2440.99
   145.3 2439.94     165 2440.09   178.1 2434.75   233.9 2431.72   289.9 2432.37
   296.5 2431.27   299.8 2428.92   306.4 2426.65   327.2 2429.09   336.1 2433.06
   342.6 2434.08   420.2 2429.81   433.7  2432.6   468.6 2433.23     485 2432.46
   501.6 2429.77   519.6 2430.32     525 2431.59   535.5 2438.91   543.8 2441.72
   555.8  2443.3   576.4 2442.82   603.3 2444.85   640.6 2455.27   670.6 2461.16
#Mann= 3 ,-1 , 0
       0     .12       0   299.8    .045       0   327.2     .12       0
Bank Sta=299.8,327.2
XS Rating Curve= 0 ,0
Exp/Cntr=0.3,0.1

Type RM Length L Ch R = 1 ,11009.7 ,237.5,206.3,164.8
XS GIS Cut Line= 4
     2035720.871        341617.9     2035958.026      341530.981
     2036016.289      341516.973     2036322.204      341388.425
#Sta/Elev= 30
       0 2496.11    12.7 2491.75    59.1 2473.17    88.9 2464.26   105.5 2460.73
     115 2457.83   127.1  2452.7     136 2450.27   187.3 2443.05   202.4  2437.8
   223.1 2437.79   233.8  2434.1   253.9 2430.74   268.2 2430.55   273.9  2427.9
   281.1 2426.38   295.2 2426.75   299.92428.314   305.3 2430.71   312.1 2431.86
   386.3 2430.48   418.8 2431.26   441.4 2433.52   476.5 2438.52   514.9 2438.76
   556.7 2440.53   574.2 2438.29   604.3 2436.73   621.7 2438.58   644.3  2443.2
#Mann= 3 ,-1 , 0
       0     .12       0   273.9    .045       0   299.9     .12       0
Bank Sta=273.9,299.9
XS Rating Curve= 0 ,0
Exp/Cntr=0.3,0.1

Type RM Length L Ch R = 1 ,10803.4 ,131,333.4,404.1
XS GIS Cut Line= 4
     2035881.727      341787.811     2036080.204      341709.674
     2036124.768      341624.8222036446.69146494341376.129895451
#Sta/Elev= 30
       0  2493.8    10.2  2488.1    20.8 2486.35    31.3 2479.98    87.7 2451.47
   101.8 2445.66   108.9 2439.37   112.4 2437.48   131.6 2437.84   147.7 2434.16
   182.9 2432.44   230.2 2433.75   234.4 2432.78   240.4 2428.62   246.6 2426.98
   262.6  2427.1   268.4  2428.8   273.7 2430.92   285.4  2431.8   299.7 2431.19
   349.8 2432.61   453.4 2431.72   490.8 2432.78   555.3 2431.17   569.5 2431.52
   585.7 2433.28   627.6 2434.52   641.9 2437.81   702.2 2466.59   715.9 2471.36
#Mann= 3 ,-1 , 0
       0     .12       0   240.4    .045       0   268.4     .12       0
#XS Ineff= 2 , 0
                             500            2450
Permanent Ineff=
       F       F
Bank Sta=240.4,268.4
XS Rating Curve= 0 ,0
Exp/Cntr=0.3,0.1

Type RM Length L Ch R = 1 ,10470.1 ,99.9,226,222.1
XS GIS Cut Line= 4
     2035904.675      341794.576     2036331.097      341715.397
     2036415.045      341734.477     2036438.894      341739.246
#Sta/Elev= 30
       0 2482.33    19.7 2471.11    29.7 2466.54      53  2454.1    66.4 2448.25
    69.7 2445.61    76.4 2436.34    79.7 2435.38    86.4  2437.3    97.2 2437.65
   106.4 2436.93   116.4 2434.57   126.4 2433.88   169.1  2434.3   186.5 2433.36
   223.2 2433.27   253.2 2434.24   279.9 2431.87     352 2431.31   380.1 2431.84
   416.8 2431.09   440.2 2432.28   450.3 2431.15   462.12426.605   477.1 2425.66
   483.9  2426.7   487.3  2428.8   500.7 2439.59   510.1 2445.24   544.1 2460.59
#Mann= 3 ,-1 , 0
       0     .12       0   462.1    .045       0   483.9     .12       0
Bank Sta=462.1,483.9
XS Rating Curve= 0 ,0
Exp/Cntr=0.3,0.1

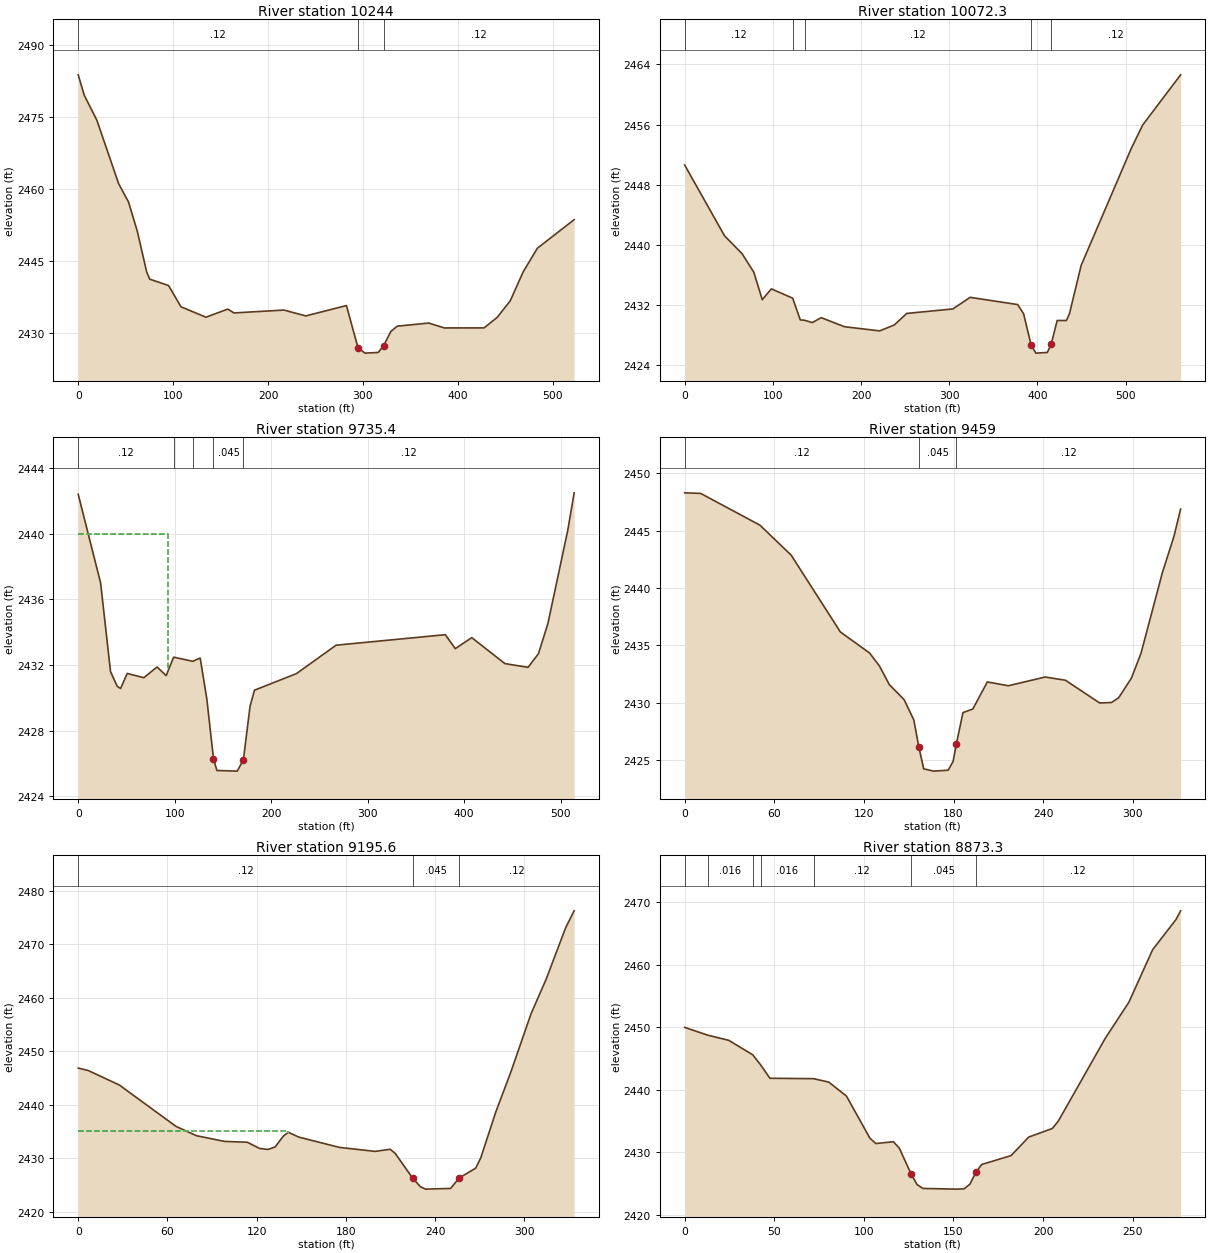
Type RM Length L Ch R = 1 ,10244   ,192.5,171.7,146.9
XS GIS Cut Line= 4
      2035891.32      341835.597     2036161.291      341821.287
     2036234.746      341835.597     2036410.826      341856.548
#Sta/Elev= 30
       0 2483.76     6.4 2479.49    19.6 2474.32    42.6 2461.06      53 2457.25
    62.3 2451.12    72.2  2442.6    75.4 2441.15    95.2 2439.82   108.3 2435.39
   134.6 2433.22   157.6 2434.91   164.1 2434.11   216.7 2434.71   239.7 2433.49
   282.6 2435.65  294.78 2426.85   302.1 2425.73   316.1 2425.87   321.7 2427.26
   329.4 2430.25   336.1 2431.35   369.3    2432   385.8 2430.98   427.6 2430.99
   441.4 2433.18   455.2 2436.65   468.8 2442.68   483.8 2447.61   522.5 2453.56
#Mann= 3 ,-1 , 0
       0     .12       0  294.78    .045       0   321.7     .12       0
#XS Ineff= 2 , 0
          279.48 2435.39
Permanent Ineff=
       F       F
Bank Sta=294.78,321.7
XS Rating Curve= 0 ,0
Exp/Cntr=0.3,0.1

Type RM Length L Ch R = 1 ,10072.3 ,338.2,336.9,281.5
XS GIS Cut Line= 4
     2035853.074      342036.712     2036219.703      341980.077
     2036282.444      341958.658     2036406.151      341939.159
#Sta/Elev= 30
       0 2450.61    45.2  2441.2    65.1 2438.82    78.4 2436.36      88  2432.7
    98.3 2434.14   122.5  2432.9   131.1 2430.01     136 2429.96   144.8 2429.65
   154.8 2430.31   181.3  2429.1   221.2 2428.55   237.8 2429.34   251.9 2430.87
   304.2 2431.47   323.8 2433.01   377.7 2432.05   384.4 2430.83   392.92426.695
   398.3 2425.59   411.3 2425.68   415.6 2426.74   422.5 2429.93   432.9 2429.93
   436.4 2430.82   449.7 2437.27   506.2 2452.73   519.5 2455.94   562.5 2462.61
#Mann= 5 ,-1 , 0
       0     .12       0   122.5    .016       0     136     .12       0
   392.9    .045       0   415.6     .12       0
Bank Sta=392.9,415.6
XS Rating Curve= 0 ,0
Exp/Cntr=0.3,0.1

Type RM Length L Ch R = 1 ,9735.4  ,348.4,276.4,237.3
XS GIS Cut Line= 3
     2035931.386      342243.892     2036133.626      342179.977
     2036422.422      342092.069
#Sta/Elev= 30
       0 2442.39    23.2    2437    33.5 2431.59    40.4  2430.7    43.9 2430.56
    50.8 2431.48      68 2431.22    81.7 2431.87    91.2 2431.35    98.9 2432.47
   118.8 2432.22   126.4 2432.42   133.3 2429.93   140.2 2426.29   143.7 2425.57
   164.8 2425.53   171.2 2426.22   178.1 2429.48   182.7 2430.46   226.2 2431.47
   267.3  2433.2   380.5 2433.84   390.8 2432.99   407.9 2433.66   442.2 2432.08
   466.2 2431.85     477 2432.68   486.8 2434.52   507.4  2440.2     514 2442.48
#Mann= 5 ,-1 , 0
       0     .12       0    98.9    .016       0   118.8     .12       0
   140.2    .045       0   171.2     .12       0
#XS Ineff= 2 , 0
              93    2440
Permanent Ineff=
       F       F
Bank Sta=140.2,171.2
XS Rating Curve= 0 ,0
Exp/Cntr=0.3,0.1

Type RM Length L Ch R = 1 ,9459    ,190.1,263.4,296.8
XS GIS Cut Line= 4
     2036264.729       342336.71     2036347.314      342272.511
     2036341.643      342174.692     2036452.811      342108.512
#Sta/Elev= 30
       0 2448.29    10.7 2448.24    50.4 2445.47    71.3 2442.86   104.2 2436.17
   123.8 2434.33   130.4  2433.2     137 2431.58   146.9 2430.27   153.4  2428.5
   156.7 2426.18     160 2424.24   166.6 2424.04   176.4 2424.12   179.7 2424.89
  181.832426.387   186.3 2429.14   192.9 2429.45   202.6 2431.81   216.7 2431.48
   241.3 2432.24   254.9 2431.96   277.8 2429.98   285.7 2430.02   290.5 2430.43
   299.1 2432.15   305.5 2434.32   319.8 2441.34   327.5 2444.48     332 2446.87
#Mann= 3 ,-1 , 0
       0     .12       0   156.7    .045       0  181.83     .12       0
Bank Sta=156.7,181.83
XS Rating Curve= 0 ,0
Exp/Cntr=0.3,0.1

Type RM Length L Ch R = 1 ,9195.6  ,306.6,322.2,336.9
XS GIS Cut Line= 3
     2036320.603       342356.46     2036506.626      342298.268
     2036641.134       342264.88
#Sta/Elev= 30
       0 2446.84     6.7 2446.39    27.7 2443.67    65.7 2435.96    79.5 2434.21
    98.3 2433.15   113.8 2432.98   121.9 2431.83   127.6 2431.64   132.4  2432.1
   137.9 2434.12   141.3 2434.85   148.4 2433.94   175.7 2432.02   199.7 2431.28
   209.8 2431.67   213.2 2430.89     225 2426.25   230.1 2424.69   233.5 2424.23
   250.4 2424.36   256.22426.311   267.3 2428.15   270.7 2430.07   280.8 2438.63
     291 2446.15   304.5 2456.98   314.6 2463.39   327.9 2473.12   333.5 2476.21
#Mann= 3 ,-1 , 0
       0     .12       0     225    .045       0   256.2     .12       0
#XS Ineff= 2 , 0
          141.07    2435
Permanent Ineff=
       F       F
Bank Sta=225,256.2
XS Rating Curve= 0 ,0
Exp/Cntr=0.3,0.1

Type RM Length L Ch R = 1 ,8873.3  ,284.5,289.6,294.9
XS GIS Cut Line= 4
2036345.66972489342592.719042641     2036443.664      342597.812
     2036536.708      342601.258     2036622.196       342605.31
#Sta/Elev= 30
       0 2449.97   12.762448.732    24.6  2447.9   37.982445.585   42.332443.997
    47.6 2441.83    71.92441.766    80.4 2441.22    90.3 2438.98   103.4 2432.24
   106.7 2431.39   116.5 2431.68   119.8 2430.65   126.4 2426.51   129.7 2424.83
     133 2424.21   151.4  2424.1   155.9 2424.14   159.2 2424.89   162.5 2426.77
   165.8 2428.04   182.2 2429.47     192 2432.42   205.2  2433.8   208.5 2434.96
   234.7  2448.2   247.9 2453.98   261.2  2462.4   274.2 2467.21   276.8 2468.61
#Mann= 7 ,-1 , 0
       0     .12       0   12.76    .016       0   37.98     .12       0
   42.33    .016       0    71.9     .12       0   126.4    .045       0
   162.5     .12       0
Bank Sta=126.4,162.5
XS Rating Curve= 0 ,0
Exp/Cntr=0.3,0.1