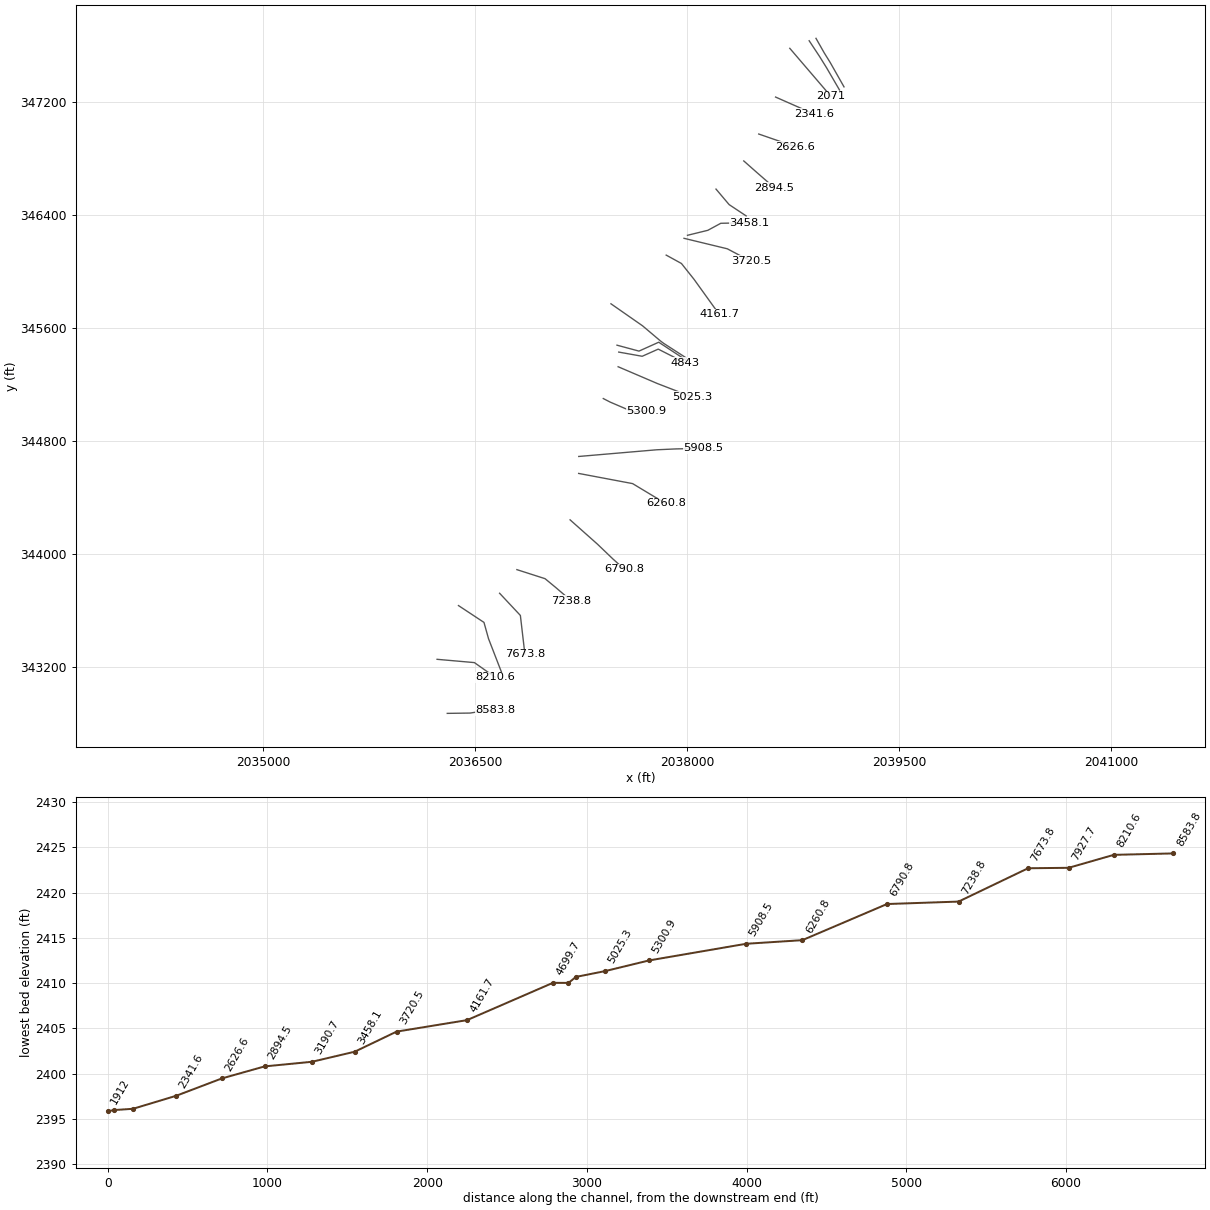
HEC-RAS study BOGGSCK.prj: BOGGSCK

--- BOGGSCK.g01 (geometry) --- (continued)

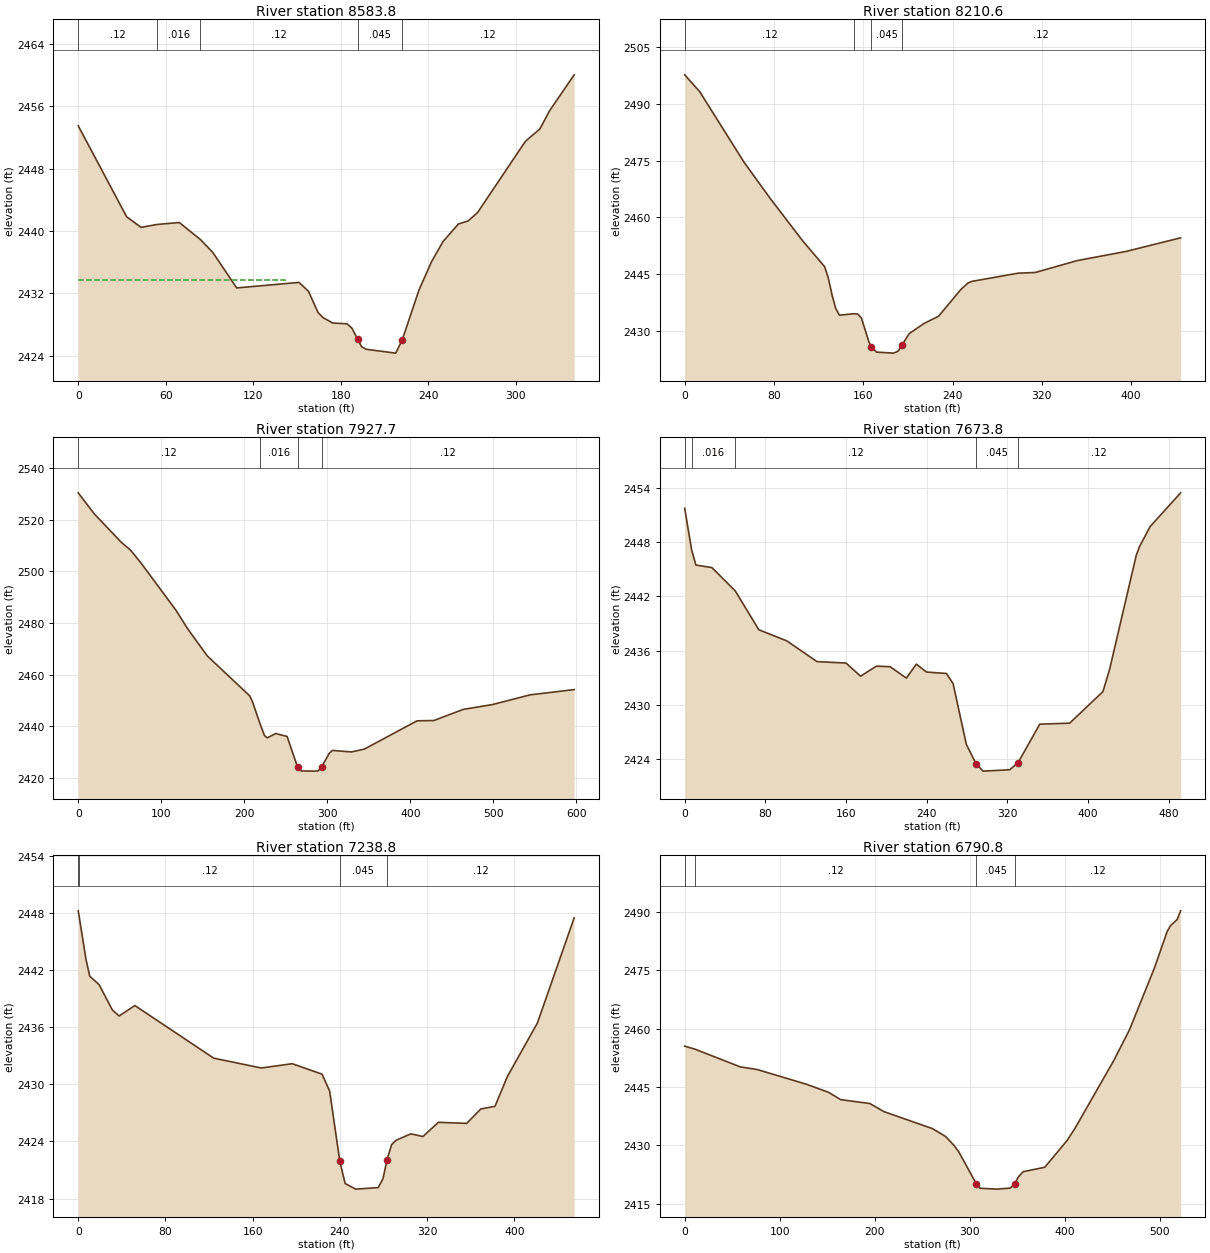
Type RM Length L Ch R = 1 ,8583.8  ,384.5,373.2,361.2
XS GIS Cut Line= 4
 2036304.1565777342870.345957359     2036465.605      342872.554
     2036548.585      342885.553     2036642.917      342892.752
#Sta/Elev= 30
       0 2453.51    33.2 2441.83    43.1 2440.47   54.122440.839    69.3 2441.09
   83.682438.925    92.3 2437.25   108.7 2432.69   151.4  2433.4   157.9 2432.26
   164.5 2429.53   167.8 2428.89   174.5 2428.19   184.4 2428.08   187.8  2427.5
   191.7 2426.07   194.4 2425.13   197.7 2424.81   217.7 2424.32   222.2 2426.01
   233.7 2432.43   242.3 2436.06   250.2 2438.65   260.7  2440.9   267.3 2441.28
   273.8 2442.35   306.7 2451.52   316.6  2453.1   323.2 2455.42   340.1 2460.05
#Mann= 5 ,-1 , 0
       0     .12       0   54.12    .016       0   83.68     .12       0
   191.7    .045       0   222.2     .12       0
#XS Ineff= 2 , 0
          142.12 2433.68
Permanent Ineff=
       F       F
Bank Sta=191.7,222.2
XS Rating Curve= 0 ,0
Exp/Cntr=0.3,0.1

Type RM Length L Ch R = 1 ,8210.6  ,346.7,283,218.7
XS GIS Cut Line= 3
     2036232.116      343253.178     2036496.007      343229.865
2036642.70505085343126.420100445
#Sta/Elev= 30
       0 2497.66    13.5  2493.2      53 2474.67      76 2465.27   105.7 2453.83
   125.4 2446.99   128.7 2444.02     132  2439.6   135.3    2436   138.6 2434.19
  152.122434.572   155.1 2434.49   158.4  2433.4     165  2427.2   167.4 2425.82
     172 2424.42   187.2 2424.16   191.3 2424.69   194.6 2426.21   201.2 2429.32
   214.3 2431.96   227.5 2433.91   247.7 2441.04   253.8 2442.66   257.2  2443.1
   298.6 2445.27   314.2 2445.46   351.8  2448.6     396 2451.05   444.4 2454.61
#Mann= 4 ,-1 , 0
       0     .12       0  152.12    .016       0   167.4    .045       0
   194.6     .12       0
Bank Sta=167.4,194.6
XS Rating Curve= 0 ,0
Exp/Cntr=0.3,0.1

Type RM Length L Ch R = 1 ,7927.7  ,262.3,253.8,245.5
XS GIS Cut Line= 4
     2036383.494       343633.67     2036563.789      343514.443
     2036595.776      343399.578     2036690.286      343155.308
#Sta/Elev= 30
       0 2530.35    19.5 2522.17      52 2511.19    63.2 2508.15    75.8 2503.14
   117.8 2484.92   131.8 2477.79   155.5 2467.27   206.6 2451.83     210 2449.48
  218.962441.056   224.3 2436.49   227.7 2435.61   237.9 2437.27   251.6 2436.13
  264.16 2424.33   268.6 2422.79   283.8 2422.73     289 2422.81   293.3 2424.48
   302.4 2429.61   306.1 2430.74   329.1 2430.15   344.6 2431.24     408 2442.17
   428.3  2442.3   463.8 2446.61   498.6 2448.45   544.3 2452.23   597.3 2454.26
#Mann= 4 ,-1 , 0
       0     .12       0  218.96    .016       0  264.16    .045       0
   293.3     .12       0
Bank Sta=264.16,293.3
XS Rating Curve= 0 ,0
Exp/Cntr=0.3,0.1

Type RM Length L Ch R = 1 ,7673.8  ,391.6,435,474.6
XS GIS Cut Line= 3
     2036674.292       343720.91     2036821.145      343563.879
     2036853.132      343289.075
#Sta/Elev= 30
       0 2451.72    6.912447.126    11.1 2445.45      27 2445.17   50.152442.593
    73.5  2438.3   101.3 2437.07   131.2 2434.78     160 2434.62   174.4 2433.17
   190.1 2434.28   203.6 2434.22   219.8 2432.96   229.7  2434.5   239.7 2433.63
   259.5 2433.47   266.1 2432.36   279.3 2425.62     289 2423.48   295.8 2422.68
   322.2 2422.83   330.4 2423.58     352 2427.87   381.7 2427.98   414.7 2431.47
   421.3 2433.93   447.7 2446.52     451  2447.5   461.4 2449.69   491.7 2453.43
#Mann= 5 ,-1 , 0
       0     .12       0    6.91    .016       0   50.15     .12       0
     289    .045       0   330.4     .12       0
Bank Sta=289,330.4
XS Rating Curve= 0 ,0
Exp/Cntr=0.3,0.1

Type RM Length L Ch R = 1 ,7238.8  ,455.4,448,442.9
XS GIS Cut Line= 4
     2036796.427      343888.118     2036995.623      343824.143
     2037071.231      343761.621     2037183.188      343665.658
#Sta/Elev= 30
       0  2448.2     .772447.684     7.2 2443.06    10.6 2441.34    19.2 2440.45
    31.3  2437.8    37.5 2437.17      52 2438.26   124.3 2432.74   167.9 2431.71
   196.3 2432.16   223.6 2431.06   230.6 2429.29   239.9 2421.92   244.8 2419.59
   254.5    2419   275.1 2419.16   279.5  2420.1   283.2 2422.08   287.4 2423.67
   291.7 2424.14   305.1  2424.8   316.1 2424.52   330.3 2426.01   356.3  2425.9
   369.2 2427.41   382.2 2427.69   393.6 2430.82   421.1 2436.43   454.8 2447.46
#Mann= 4 ,-1 , 0
       0    .016       0     .77     .12       0   239.9    .045       0
   283.2     .12       0
Bank Sta=239.9,283.2
XS Rating Curve= 0 ,0
Exp/Cntr=0.3,0.1

Type RM Length L Ch R = 1 ,6790.8  ,517.3,530,542.6
XS GIS Cut Line= 4
      2037172.66      344240.758     2037366.391      344068.413
     2037476.631      343962.665     2037558.598      343889.208
#Sta/Elev= 30
       0 2455.47   11.352454.655    58.5 2450.14    76.4 2449.46   128.2 2445.68
   151.5  2443.6   164.3 2441.72     195 2440.72   209.6 2438.66   260.9 2434.27
   274.6 2432.28   284.2 2429.79   288.9 2428.16   307.1 2420.05   310.9 2418.95
   329.1 2418.73   342.8    2419   347.3 2420.03   351.2 2421.85   356.4 2423.21
   379.1 2424.35   402.7 2431.26     411  2434.4   451.5 2451.67   468.3 2459.68
   494.7 2475.66   507.9 2484.93   511.4 2486.42   518.4    2488   522.1 2490.24
#Mann= 4 ,-1 , 0
       0    .016       0   11.35     .12       0   307.1    .045       0
   347.3     .12       0
Bank Sta=307.1,347.3
XS Rating Curve= 0 ,0
Exp/Cntr=0.3,0.1

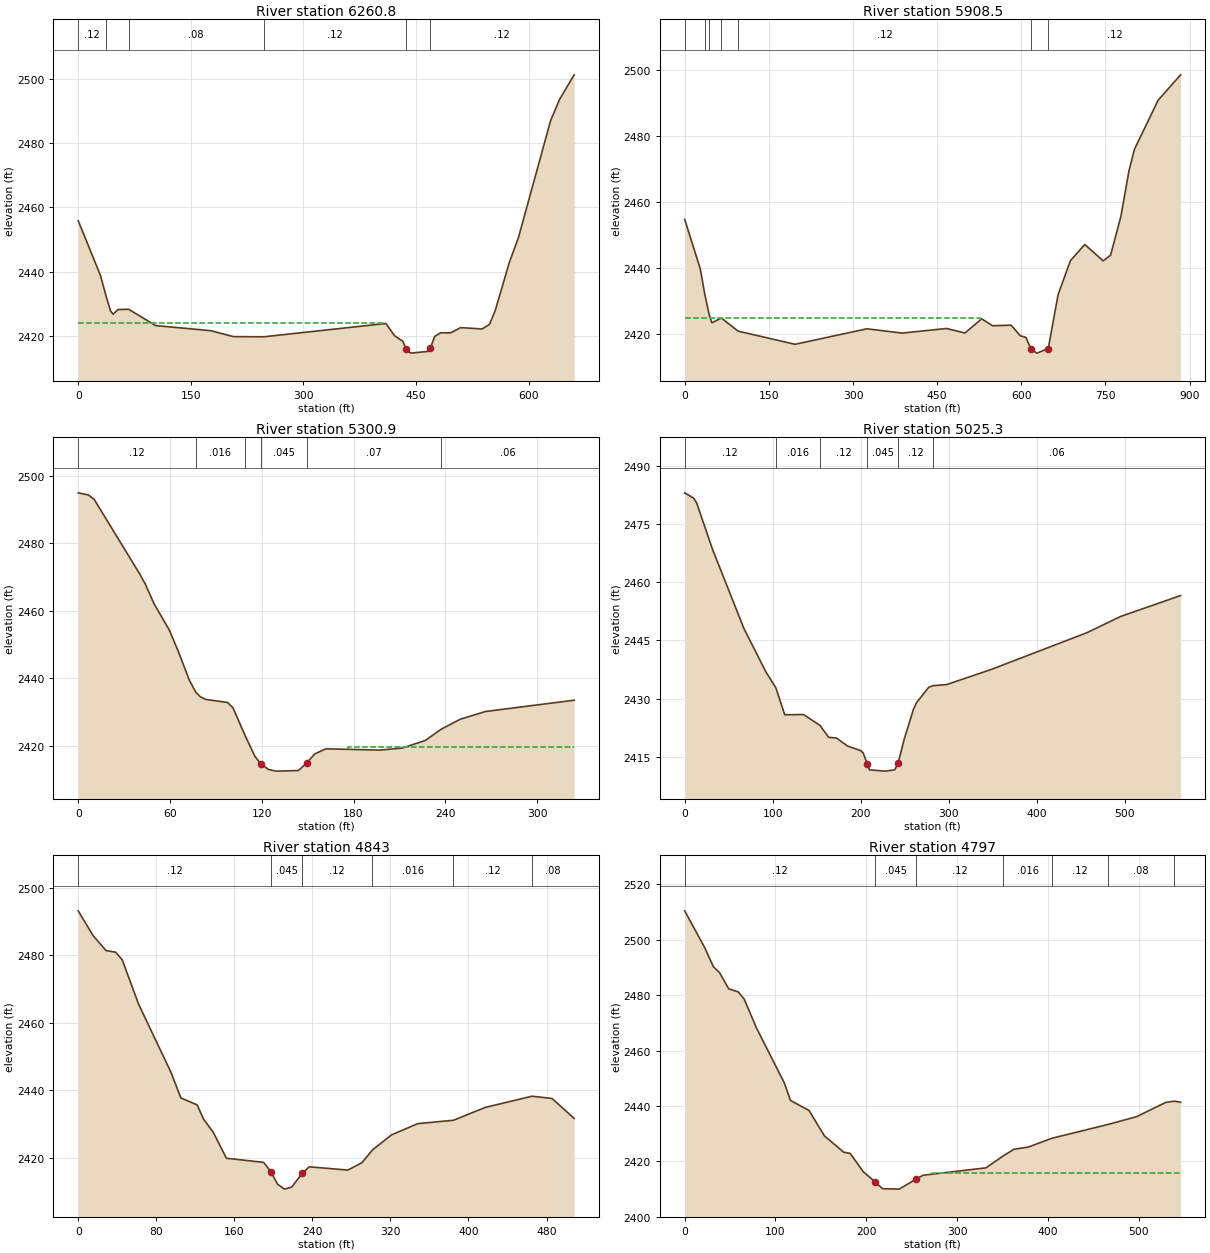
Type RM Length L Ch R = 1 ,6260.8  ,320.8,352.3,383.2
XS GIS Cut Line= 4
     2037233.378      344569.319     2037614.674      344497.323
     2037774.261      344401.125     2037849.223      344358.663
#Sta/Elev= 30
       0 2455.91    29.7 2438.85   37.012432.528    43.1 2427.81    46.4 2426.85
    53.1 2428.28   67.072428.379   103.2  2423.3   176.6 2421.71   206.7 2419.87
  247.422419.823   409.8 2423.95   421.3 2420.15   432.4 2418.41   436.6 2416.06
     443 2414.74   466.1 2415.28  469.09 2416.42   474.9 2419.96   482.8 2421.07
   495.9 2421.04   509.4 2422.67   537.8 2422.25   547.7 2423.65   555.4 2427.99
   574.5 2443.16   586.4 2450.71     629 2486.88     641 2493.56   660.5 2501.23
#Mann= 6 ,-1 , 0
       0     .12       0   37.01    .016       0   67.07     .08       0
  247.42     .12       0   436.6    .045       0  469.09     .12       0
#XS Ineff= 2 , 0
          406.78 2424.12
Permanent Ineff=
       F       F
Bank Sta=436.6,469.09
XS Rating Curve= 0 ,0
Exp/Cntr=0.3,0.1

Type RM Length L Ch R = 1 ,5908.5  ,632.8,607.6,578
XS GIS Cut Line= 4
      2037233.95       344689.48     2037785.032      344736.799
     2037921.432      344742.908     2038115.744      344747.178
#Sta/Elev= 30
       0 2454.79    27.8 2439.84   35.932432.082   43.952425.735    48.5 2423.52
   65.572424.948   95.222420.991   196.7 2417.01     325  2421.7   387.7  2420.4
   466.7 2421.79   499.6 2420.43   529.3 2424.71     549 2422.62   581.9  2422.8
   598.3 2419.57   608.1 2419.13   617.5  2415.5   627.9 2414.34  648.06 2415.73
   665.6 2432.02   687.6 2442.31   713.2  2447.2     746 2442.23   759.2 2443.97
   777.5 2455.65     792 2469.52   801.8 2476.01     844 2490.85     884  2498.5
#Mann= 7 ,-1 , 0
       0     .12       0   35.93    .016       0   43.95     .12       0
   65.57    .016       0   95.22     .12       0   617.5    .045       0
  648.06     .12       0
#XS Ineff= 2 , 0
          526.29 2424.87
Permanent Ineff=
       F       F
Bank Sta=617.5,648.06
XS Rating Curve= 0 ,0
Exp/Cntr=0.3,0.1

Type RM Length L Ch R = 1 ,5300.9  ,275.8,275.6,273.7
XS GIS Cut Line= 4
     2037407.493      345099.559     2037456.538      345074.268
     2037620.152      345004.083     2037710.666       345013.41
#Sta/Elev= 30
       0 2494.99     6.8 2494.34    10.5    2493      40  2471.1    43.7 2468.09
    49.6  2462.1    59.5 2454.36    65.5 2447.92    72.6  2439.5    76.92435.874
    79.8 2434.56    83.3 2433.76    97.6 2432.86   101.2 2431.26  109.04  2423.1
   115.5 2416.89   119.4 2414.64   124.4 2412.99   129.4  2412.5     144 2412.67
   149.3 2414.92   154.7 2417.62   161.9 2419.12   196.9 2418.73   211.9 2419.34
   226.9  2421.6  237.272424.911   249.7 2427.88   266.2 2430.17   324.2 2433.52
#Mann= 6 ,-1 , 0
       0     .12       0    76.9    .016       0  109.04     .12       0
   119.4    .045       0   149.3     .07       0  237.27     .06       0
#XS Ineff= 2 , 0
                          176.29         2419.72
Permanent Ineff=
       F       F
Bank Sta=119.4,149.3
XS Rating Curve= 0 ,0
Exp/Cntr=0.5,0.3

Type RM Length L Ch R = 1 ,5025.3  ,182.3,182.3,182.3
XS GIS Cut Line= 3
      2037512.44       345324.82     2037789.646      345205.984
     2038033.862      345111.504
#Sta/Elev= 30
       0 2483.03    10.2 2481.66    13.7 2480.38    31.6 2468.49    67.3 2448.08
    92.3 2436.89  103.632432.779   113.7 2425.85   135.1  2425.9  153.71 2423.11
   163.6 2420.03   172.5 2419.85     185 2417.79     200  2416.6   202.9 2415.97
   207.5 2413.19     210 2411.65   227.5 2411.32   238.6 2411.65   242.5 2413.34
   249.3 2419.43     260  2427.3   263.6 2429.01   277.4 2432.94  282.26 2433.34
   297.7 2433.62   348.6 2437.54   457.2    2447   495.2 2451.16   563.5 2456.56
#Mann= 6 ,-1 , 0
       0     .12       0  103.63    .016       0  153.71     .12       0
   207.5    .045       0   242.5     .12       0  282.26     .06       0
Bank Sta=207.5,242.5
XS Rating Curve= 0 ,0
Exp/Cntr=0.5,0.3

Type RM Length L Ch R = 1 ,4843    ,46.2,46.2,46.2
XS GIS Cut Line= 4
2037516.64794226345428.5701620842037682.52770469345398.886415123
2037796.02438425345449.5233952332037988.09568811345351.741640538
#Sta/Elev= 30
       0 2493.23    15.2 2485.91    28.5 2481.44    38.5 2480.94    45.2 2478.64
    61.9 2465.55    95.2 2445.24   105.2 2437.73   121.9 2435.67   128.5 2431.43
   138.5  2427.5   151.9 2419.84   190.1 2418.61   197.3 2415.89   204.4 2412.11
   211.6 2410.68   218.8 2411.28   229.6 2415.36   236.8  2417.3   276.3 2416.33
   290.7  2418.5   301.6 2422.28   301.6 2422.31   321.1 2426.77     348 2430.11
   384.6  2431.1   417.3 2434.93   465.1 2438.24   485.7 2437.56   508.3 2431.66
#Mann= 6 ,-1 , 0
       0     .12       0   197.3    .045       0   229.6     .12       0
   301.6    .016       0   384.6     .12       0   465.1     .08       0
#XS Ineff= 2 , 0
                          238.21         2416.39
Permanent Ineff=
       F       F
Bank Sta=197.3,229.6
XS Rating Curve= 0 ,0
Exp/Cntr(USF)=0,0
Exp/Cntr=0.5,0.3

Type RM Length L Ch R = 1 ,4797    ,97.1,97.1,97.1
XS GIS Cut Line= 4
2037504.42522292345477.4610394322037659.82836878345435.554573134
2037799.51658977345498.414272581 2037993.3339964345370.948770925
#Sta/Elev= 30
       0 2510.42    21.8 2497.32    31.6 2490.28    38.4 2488.12    48.5 2482.28
    58.9 2481.19    65.5  2478.6    79.1 2468.14   109.7 2448.35   116.5 2442.01
   136.9 2438.41   153.9 2429.22   175.1 2423.35   182.3 2422.89   196.6  2416.3
   209.3 2412.75   217.9 2410.18   236.2 2410.02   255.2 2413.71   262.6 2415.03
   331.8  2417.7   350.6 2421.97   362.6 2424.41   378.3 2425.19   404.4 2428.37
   465.9 2433.33   497.6 2436.16   529.8 2441.32   539.3 2441.74   546.1 2441.38
#Mann= 7 ,-1 , 0
       0     .12       0   209.3    .045       0   255.2     .12       0
   350.6    .016       0   404.4     .12       0   465.9     .08       0
   539.3     .12       0
#XS Ineff= 2 , 0
                          272.38          2415.8
Permanent Ineff=
       F       F
Bank Sta=209.3,255.2
XS Rating Curve= 0 ,0
Exp/Cntr(USF)=0,0
Exp/Cntr=0.5,0.3

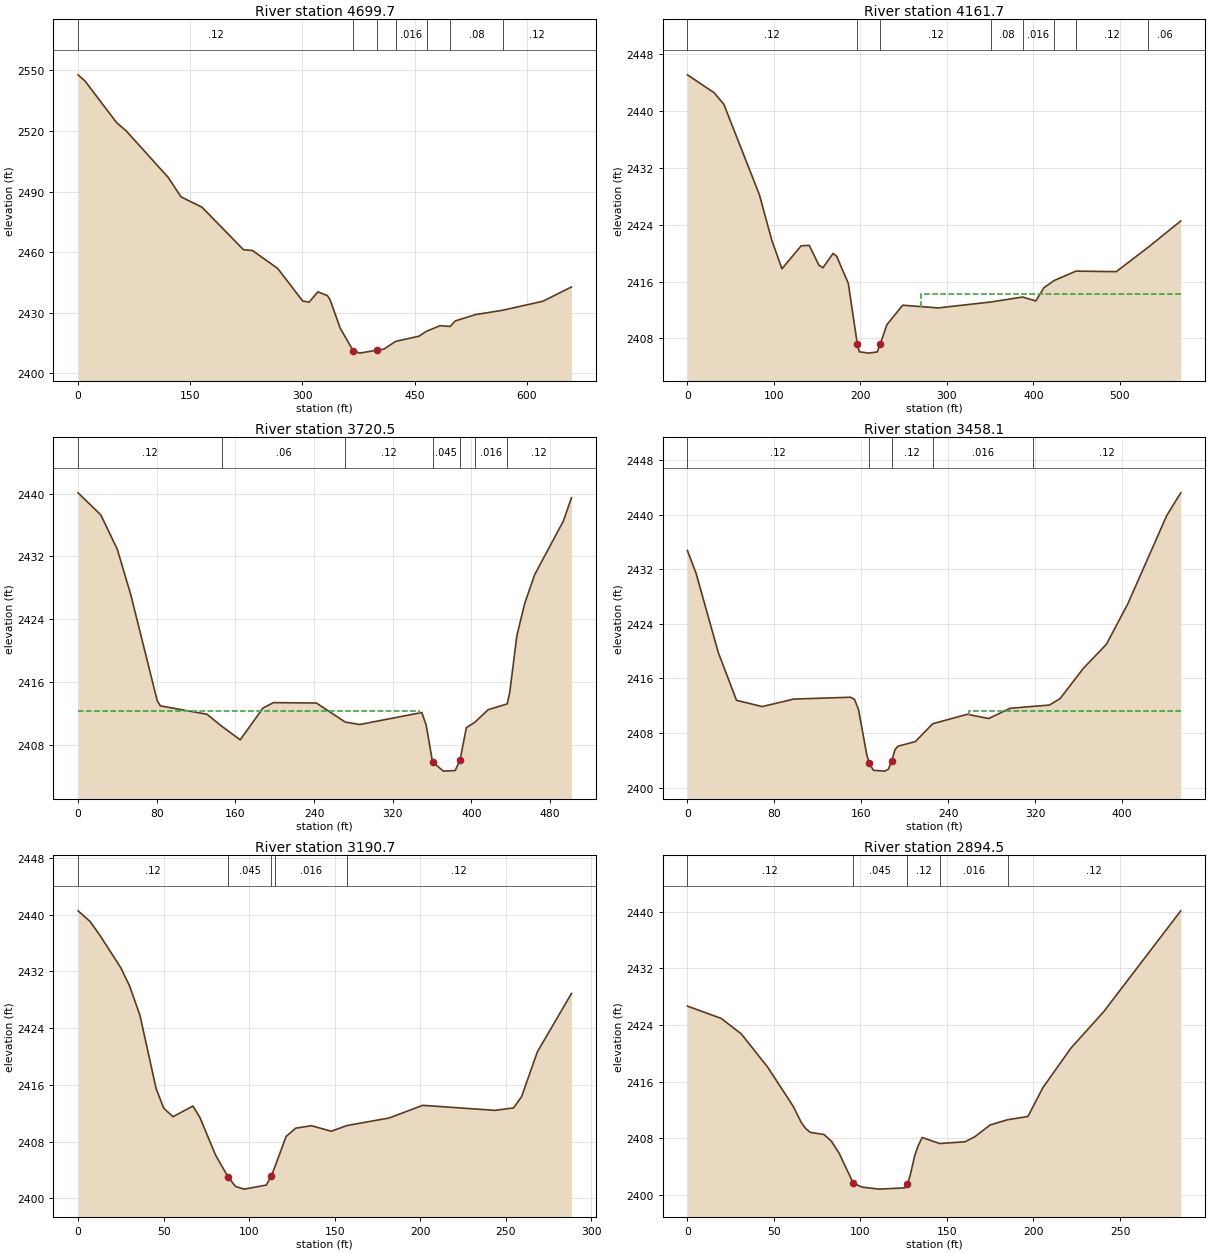
Type RM Length L Ch R = 1 ,4699.7  ,561.2,538,529.5
XS GIS Cut Line= 5
     2037461.766      345770.422       2037685.4      345614.375
     2037812.064      345507.122     2037834.389      345490.517
     2037996.751      345385.521
#Sta/Elev= 30
       0 2547.73     9.2  2544.7    51.7 2523.99    64.4 2519.96   120.5 2496.99
   137.7 2487.33   165.7 2482.24   221.2 2461.19   233.2 2460.81     267 2451.91
   300.4 2435.82     309 2435.23   320.7 2440.37   333.4 2438.48   336.9 2436.54
   350.6 2422.34   367.8 2411.29   376.4 2410.03   399.8  2411.5   409.1 2412.03
   424.72415.856   455.8 2418.39   466.1 2420.87   484.1  2423.6  497.562423.229
   504.4 2425.96   531.5  2429.1  567.91 2431.25   621.7 2435.71   659.8 2442.77
#Mann= 7 ,-1 , 0
       0     .12       0   367.8    .045       0   399.8     .12       0
   424.7    .016       0   466.1     .12       0  497.56     .08       0
  567.91     .12       0
Bank Sta=367.8,399.8
XS Rating Curve= 0 ,0
Exp/Cntr=0.3,0.1

Type RM Length L Ch R = 1 ,4161.7  ,412.8,441.2,462.5
XS GIS Cut Line= 4
      2037852.34      346115.193     2037960.043      346055.957
     2038048.522      345944.601     2038226.532      345696.716
#Sta/Elev= 30
       0 2445.12    30.9  2442.6    42.1 2440.98    83.3 2428.21    97.5 2421.84
   109.3 2417.79   131.5 2421.03   140.9 2421.09     152  2418.3   156.7 2417.94
   168.4 2419.96   172.6 2419.55     186 2415.74   196.4 2407.23   198.7  2406.1
   209.5 2405.91   219.5 2406.08   222.8 2407.16   230.6 2409.91   248.8 2412.66
     290 2412.28  351.15 2413.12  387.522413.814   402.8 2413.26   412.2 2415.13
  423.882416.134  449.142417.463   495.8 2417.39  532.972420.855   570.3 2424.53
#Mann= 8 ,-1 , 0
       0     .12       0   196.4    .045       0   222.8     .12       0
  351.15     .08       0  387.52    .016       0  423.88     .08       0
  449.14     .12       0  532.97     .06       0
#XS Ineff= 2 , 0
                             270         2414.26
Permanent Ineff=
       F       F
Bank Sta=196.4,222.8
XS Rating Curve= 0 ,0
Exp/Cntr=0.5,0.3

Type RM Length L Ch R = 1 ,3720.5  ,214.6,262.4,315.3
XS GIS Cut Line= 4
     2037978.351      346234.132      2038284.48      346159.933
     2038376.081      346111.515     2038450.973      346075.321
#Sta/Elev= 30
       0 2440.11    23.1  2437.3    39.9 2432.91    53.5 2427.17    80.5 2413.61
    83.8 2412.95   131.1 2411.89  146.392410.334   164.9 2408.63     188 2412.67
   198.6 2413.37   242.4 2413.32  271.772410.892   286.4 2410.58   349.6 2412.11
   354.1 2410.48   360.5 2405.82   371.5 2404.64   383.6 2404.72   388.5 2406.05
   394.9 2410.18  403.362410.846   417.1 2412.47  436.442413.206     439 2414.64
   446.3 2421.92   454.4 2426.07   464.5 2429.71   493.5 2436.49   501.8 2439.47
#Mann= 7 ,-1 , 0
       0     .12       0  146.39     .06       0  271.77     .12       0
   360.5    .045       0   388.5     .12       0  403.36    .016       0
  436.44     .12       0
#XS Ineff= 2 , 0
          346.64 2412.27
Permanent Ineff=
       F       F
Bank Sta=360.5,388.5
XS Rating Curve= 0 ,0
Exp/Cntr=0.5,0.3

Type RM Length L Ch R = 1 ,3458.1  ,333.4,267.4,196.9
XS GIS Cut Line= 4
     2038002.838      346255.535     2038146.783      346290.867
     2038238.385      346340.593     2038439.908      346344.519
#Sta/Elev= 30
       0 2434.76       8 2431.42    28.4 2419.82    45.2  2412.8    68.8 2411.88
    97.9 2412.98   150.3 2413.25   153.8 2412.92   157.5 2411.43     165 2404.88
   167.2 2403.63   171.2 2402.54   181.7 2402.42     185 2402.71  187.96 2403.89
   191.1 2405.58   193.8 2406.07   209.8 2406.75  225.742409.366   257.6 2410.75
   277.3 2410.13     297 2411.63   317.62411.907   333.1  2412.1   342.9 2413.04
   364.3 2417.47   385.6 2421.01   405.3 2426.94   441.1 2439.88     454 2443.21
#Mann= 5 ,-1 , 0
       0     .12       0   167.2    .045       0  187.96     .12       0
  225.74    .016       0   317.6     .12       0
#XS Ineff= 2 , 0
                          259.31         2411.26
Permanent Ineff=
       F       F
Bank Sta=167.2,187.96
XS Rating Curve= 0 ,0
Exp/Cntr=0.3,0.1

Type RM Length L Ch R = 1 ,3190.7  ,288.6,296.2,302
XS GIS Cut Line= 3
     2038204.479      346582.759     2038297.259      346472.887
     2038417.604      346392.871
#Sta/Elev= 30
       0 2440.53       7 2439.03    12.9 2437.03      25 2432.49    30.1 2429.94
    36.2 2425.76    45.6 2415.47    50.1 2412.69    55.5 2411.52    67.1 2413.02
    71.1 2411.45    80.4 2406.08    87.7 2403.01      92 2401.68    97.1 2401.31
     110 2401.88     113  2403.2  114.832404.349   121.6 2408.75   127.2  2409.9
   136.3 2410.25     148 2409.47  157.172410.274   181.7 2411.33   201.4 2413.12
   243.7 2412.41   254.5 2412.76   259.2 2414.36   268.4 2420.66   288.3 2428.88
#Mann= 5 ,-1 , 0
       0     .12       0    87.7    .045       0     113     .12       0
  114.83    .016       0  157.17     .12       0
Bank Sta=87.7,113
XS Rating Curve= 0 ,0
Exp/Cntr=0.3,0.1

Type RM Length L Ch R = 1 ,2894.5  ,247.2,267.9,288.2
XS GIS Cut Line= 3
      2038400.94      346781.974     2038485.129      346707.526
     2038615.189      346593.915
#Sta/Elev= 30
       0 2426.65    19.5 2424.92    31.1 2422.74    46.3 2418.07    61.1 2412.52
    65.9 2410.17    68.3 2409.38      71 2408.82      79 2408.51    83.3 2407.54
    87.7 2405.87    95.8 2401.67   100.8 2401.09   110.7  2400.8   125.6 2400.98
   127.1 2401.46   128.7 2402.71   131.4 2405.55   133.4 2406.95   135.7 2408.09
  145.782407.241   160.5 2407.49   166.3 2408.23     175 2409.87     1852410.601
   196.8 2411.06   205.4 2415.12   221.7 2420.74   240.4 2425.81   285.1 2440.11
#Mann= 5 ,-1 , 0
       0     .12       0    95.8    .045       0   127.1     .12       0
  145.78    .016       0     185     .12       0
Bank Sta=95.8,127.1
XS Rating Curve= 0 ,0
Exp/Cntr=0.3,0.1

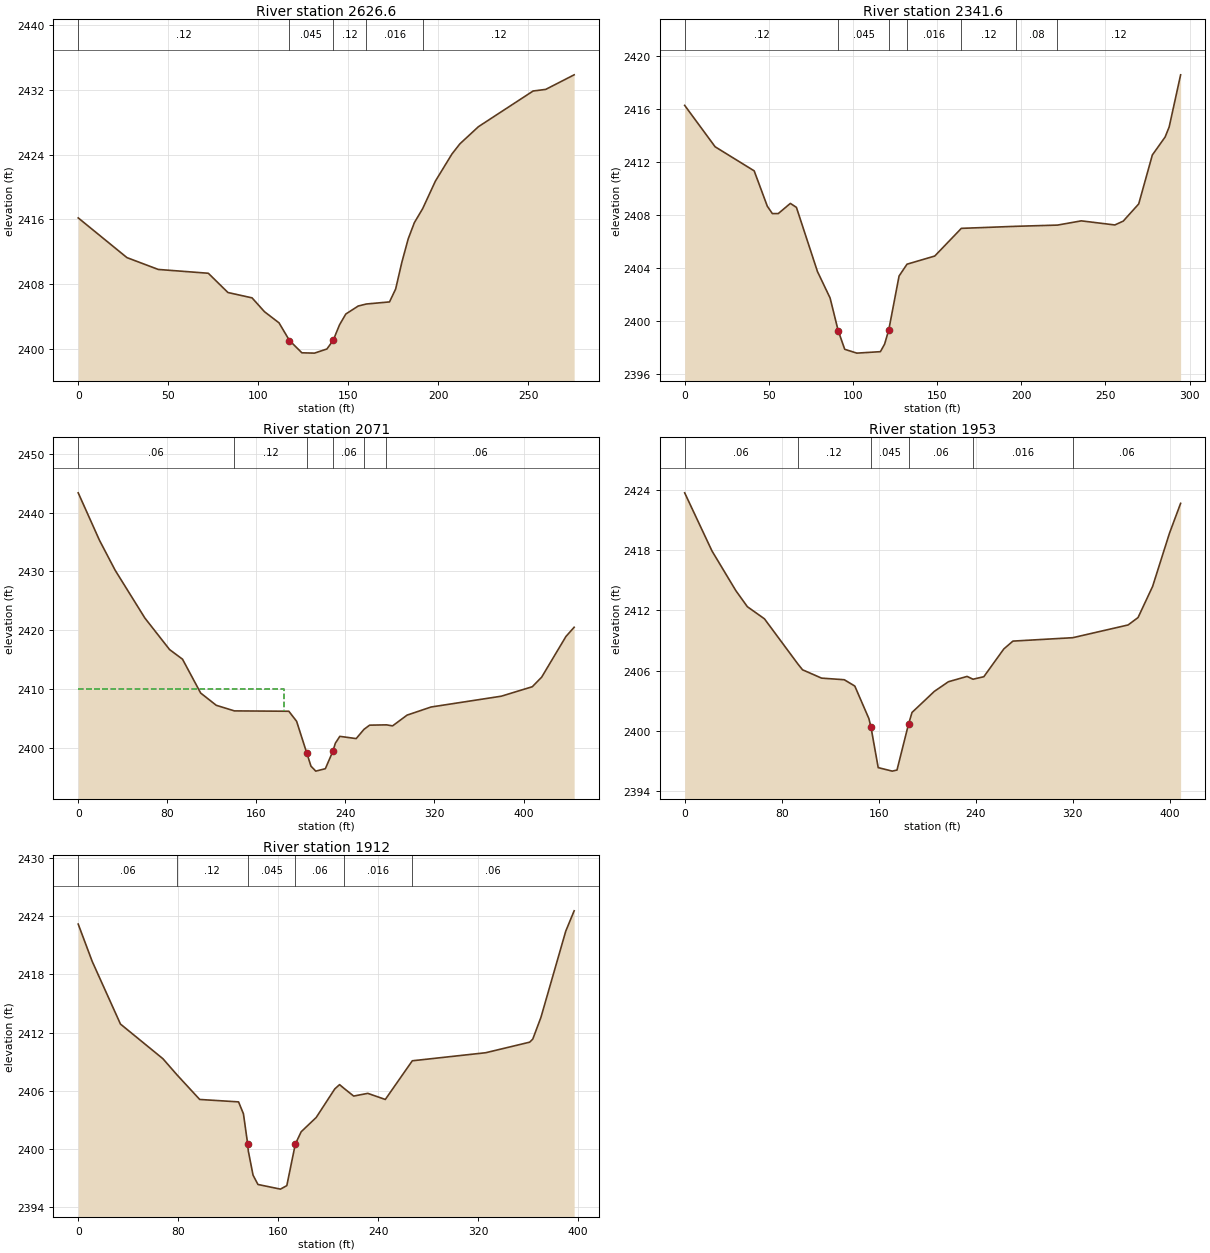
Type RM Length L Ch R = 1 ,2626.6  ,288.6,285,280.4
XS GIS Cut Line= 2
     2038506.646      346972.642     2038767.055      346882.349
#Sta/Elev= 30
       0 2416.18    27.1 2411.27    44.5 2409.81    72.3 2409.34    83.2 2406.96
    96.6  2406.3   103.5 2404.59   111.6 2403.21   117.4 2401.03   124.3 2399.51
   131.3 2399.47   138.2 2399.98   141.7 2401.05   145.2 2402.96   148.7  2404.3
   155.6 2405.29  160.15 2405.54     173  2405.8   176.4 2407.39   179.9 2410.74
   183.4  2413.6   186.8 2415.59  191.422417.327   198.5 2420.73   207.7 2424.08
   212.1 2425.33   222.4 2427.45   252.8 2431.86   259.8 2432.06   275.6 2433.86
#Mann= 5 ,-1 , 0
       0     .12       0   117.4    .045       0   141.7     .12       0
  160.15    .016       0  191.42     .12       0
Bank Sta=117.4,141.7
XS Rating Curve= 0 ,0
Exp/Cntr=0.5,0.3

Type RM Length L Ch R = 1 ,2341.6  ,294.6,270.6,246.9
XS GIS Cut Line= 2
     2038625.727       347234.36     2038895.297      347115.279
#Sta/Elev= 30
       0 2416.29    18.1 2413.16    41.3 2411.34    49.1 2408.67    52.1 2408.11
    55.6 2408.11    62.8 2408.88    66.4 2408.58    78.9 2403.73    86.4 2401.73
    91.2 2399.27    95.1 2397.85   102.3 2397.56   116.3 2397.67   118.8 2398.24
   121.3 2399.33   127.4 2403.39  132.112404.283   148.6  2404.9   164.42406.992
  196.692407.147  221.522407.239   235.7 2407.56   255.6 2407.25   260.6 2407.54
   269.8 2408.84   277.9 2412.54   285.5  2413.9   287.9 2414.66   294.7  2418.6
#Mann= 7 ,-1 , 0
       0     .12       0    91.2    .045       0   121.3     .12       0
  132.11    .016       0   164.4     .12       0  196.69     .08       0
  221.52     .12       0
Bank Sta=91.2,121.3
XS Rating Curve= 0 ,0
Exp/Cntr=0.3,0.1

Type RM Length L Ch R = 1 ,2071    ,117.5,117.5,117.5
XS GIS Cut Line= 2
2038726.28452496347579.4854944522039015.85121006347240.915216491
#Sta/Elev= 30
       0 2443.34    19.1 2435.29    33.2  2430.2    59.9 2422.09    82.1 2416.74
    93.7 2415.11     110 2409.37     124 2407.29   140.3 2406.34   189.2 2406.28
   196.2 2404.57   205.4 2399.14   209.1 2396.96   213.4 2396.12     222 2396.53
   228.7 2399.46     231 2400.86     235 2402.02   249.7 2401.64   256.7 2403.21
   261.8 2403.92   276.9 2403.97   282.4  2403.8   295.4 2405.62     317    2407
     380 2408.83   407.9 2410.44   416.3 2412.06   438.1 2418.96   445.5 2420.53
#Mann= 6 ,-1 , 0
       0     .06       0   140.3     .12       0   205.4    .045       0
   228.7     .06       0   256.7    .016       0   276.9     .06       0
#XS Ineff= 2 , 0
          184.85    2410
Permanent Ineff=
       F       F
Bank Sta=205.4,228.7
XS Rating Curve= 0 ,0
Exp/Cntr=0.5,0.3

Type RM Length L Ch R = 1 ,1953    ,41.6,41.6,41.6
XS GIS Cut Line= 4
2038863.35274633347632.9871838092038936.67229976347521.862235634
2038987.07949275347440.5233560432039077.58331652347284.719304994
#Sta/Elev= 30
       0 2423.72    22.5 2417.93    42.2 2413.97    51.7 2412.37    65.8 2411.16
    93.3 2406.67    97.2 2406.08   112.9 2405.25   131.6 2405.09   140.3 2404.46
   151.9 2401.22   153.6 2400.39   159.6 2396.33   171.2 2395.98   175.1 2396.09
   184.6 2400.66   187.5 2401.83   205.9 2403.93   217.5 2404.89   232.9 2405.42
   237.8 2405.14   246.7 2405.39   263.2 2408.16   270.7 2408.94   320.1 2409.28
   365.7 2410.55   373.9 2411.29   385.9 2414.39   399.8 2419.69     409 2422.67
#Mann= 6 ,-1 , 0
       0     .06       0    93.3     .12       0   153.6    .045       0
   184.6     .06       0   237.8    .016       0   320.1     .06       0
#XS Ineff= 2 , 0
          120.27 2404.23   225.5         2404.27
Permanent Ineff=
       F       F
Bank Sta=153.6,184.6
XS Rating Curve= 0 ,0
Exp/Cntr(USF)=0,0
Exp/Cntr=0.5,0.3

Type RM Length L Ch R = 1 ,1912    ,126.6,126.6,126.6
XS GIS Cut Line= 4
2038911.46870327347650.1714541452038969.89522241347547.065832128
2039011.13747122347480.6199868272039109.66062115 347306.48604742
#Sta/Elev= 30
       0 2423.19    11.2 2419.34    33.8 2412.88    67.8  2409.3    79.1 2407.63
    97.2  2405.1   128.3 2404.85   132.2 2403.62  135.54 2400.55   136.1 2399.78
   139.9 2397.29   143.8 2396.33   161.8 2395.85   166.9 2396.21   173.7 2400.49
   178.4 2401.77   190.4 2403.24   205.3 2406.19   209.1 2406.63   212.9 2406.22
   220.4 2405.45   231.7 2405.73   245.7  2405.1   267.3 2409.09     326 2409.92
   361.2 2411.01   363.7 2411.33   370.2 2413.56   390.1 2422.47   396.8 2424.56
#Mann= 6 ,-1 , 0
       0     .06       0    79.1     .12       0  135.54    .045       0
   173.7     .06       0   212.9    .016       0   267.3     .06       0
#XS Ineff= 2 , 0
          120.71 2404.31  202.67         2404.27
Permanent Ineff=
       F       F
Bank Sta=135.54,173.7
XS Rating Curve= 0 ,0
Exp/Cntr(USF)=0,0
Exp/Cntr=0.5,0.3