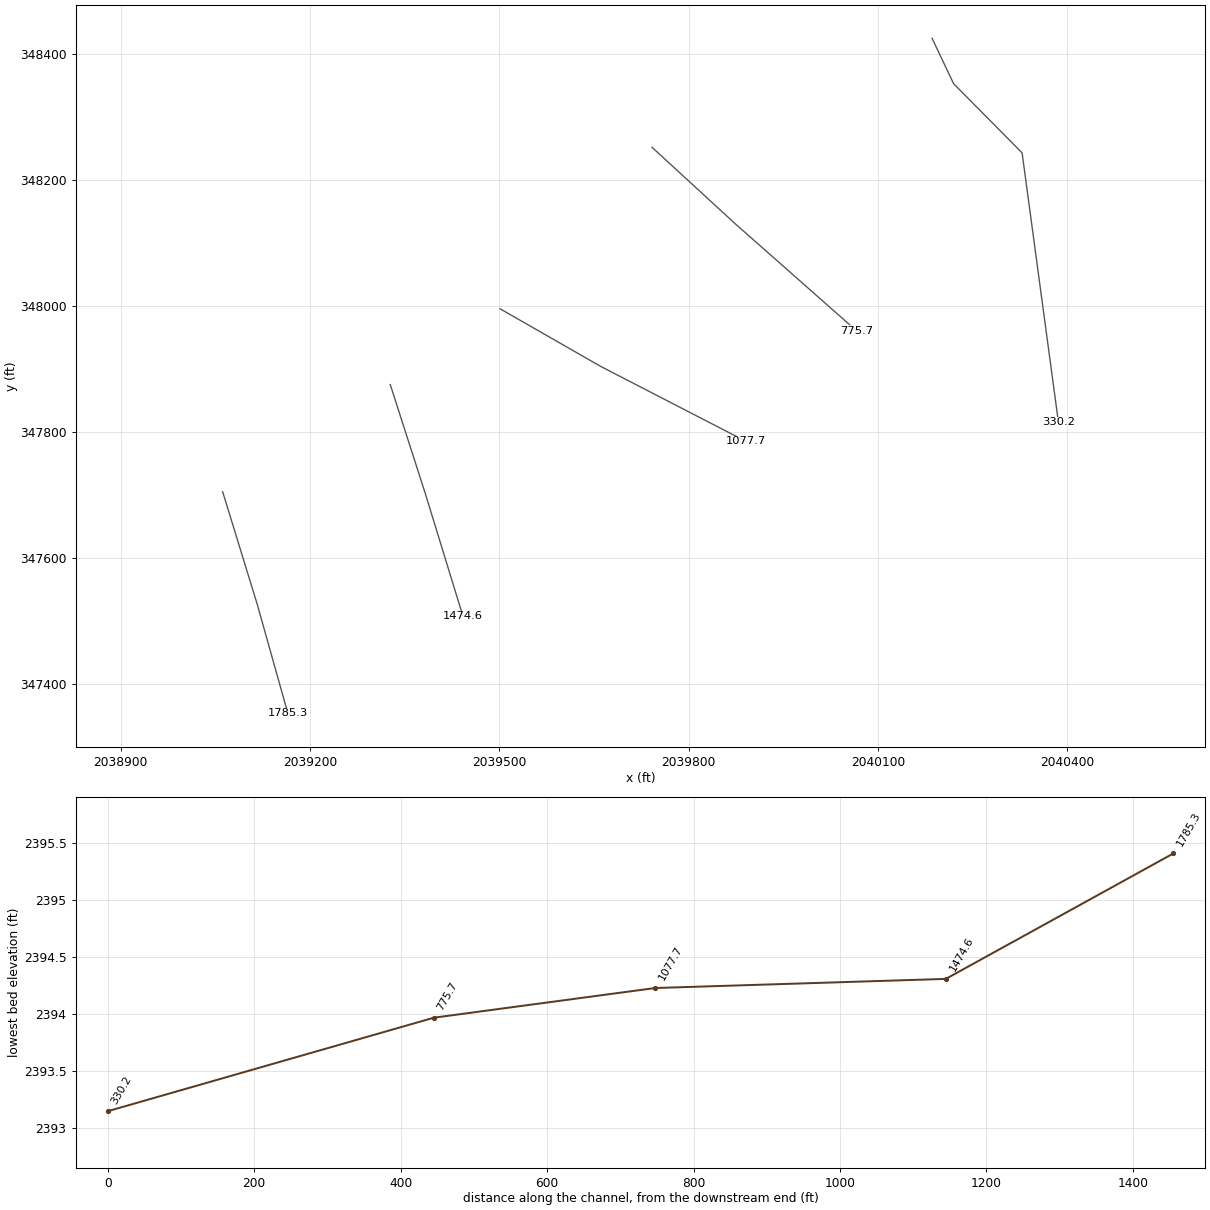
HEC-RAS study BOGGSCK.prj: BOGGSCK

--- BOGGSCK.g01 (geometry) --- (continued)

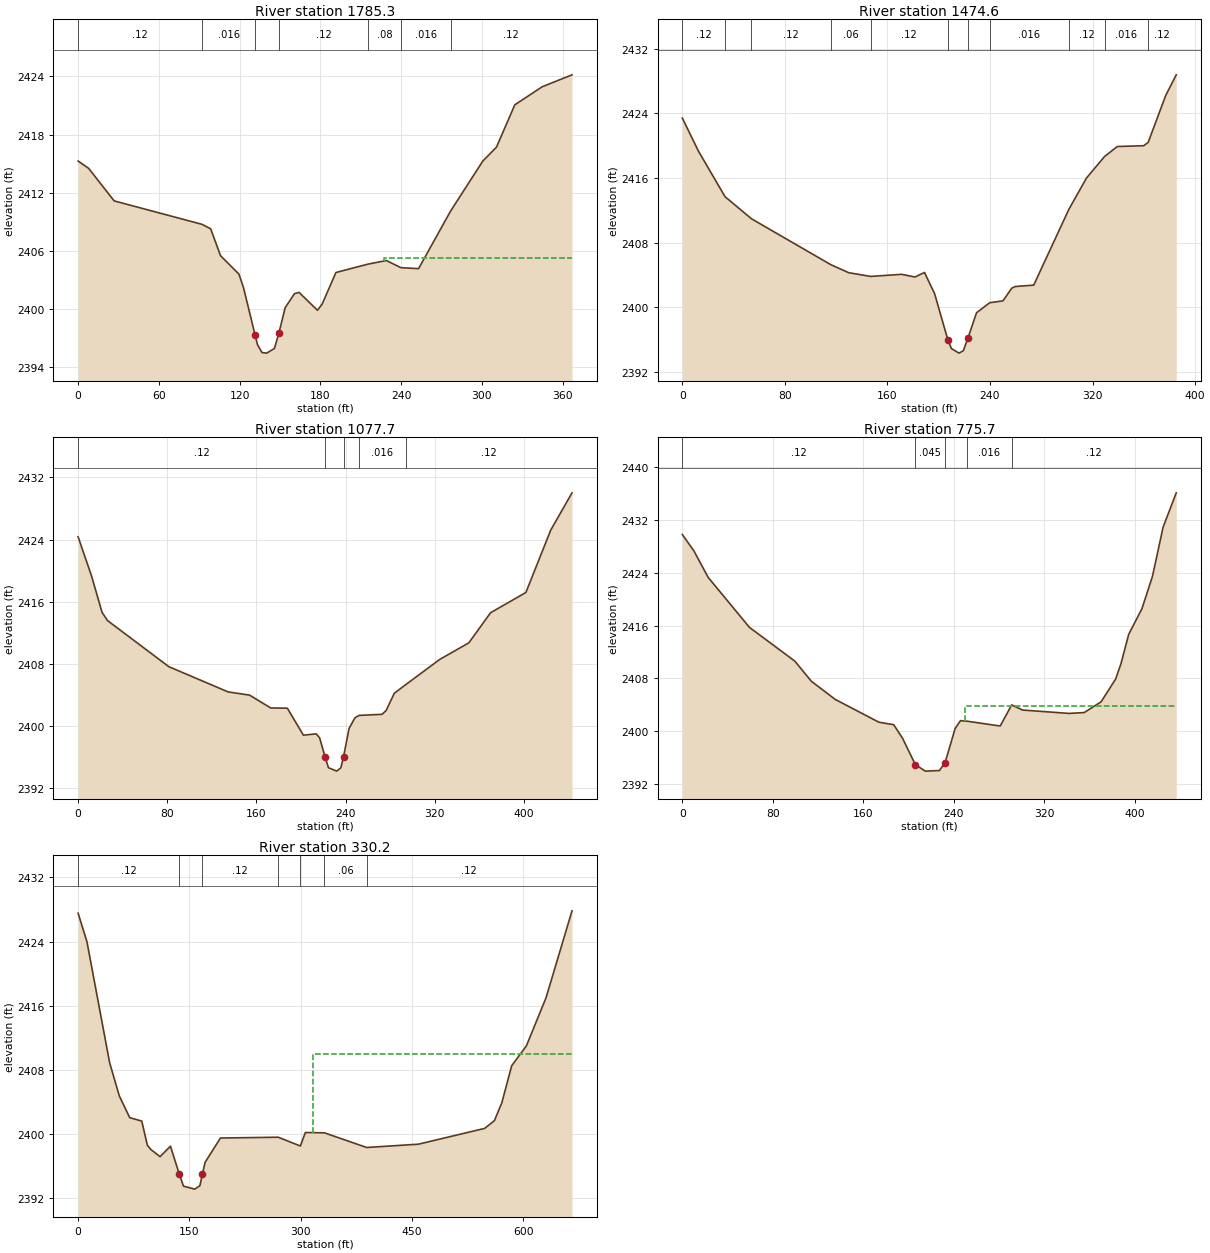
Type RM Length L Ch R = 1 ,1785.3  ,310.3,310.8,311.1
XS GIS Cut Line= 3
     2039061.488      347705.453     2039116.449      347526.176
     2039164.866      347353.442
#Sta/Elev= 30
       0 2415.26     7.8 2414.51    26.8 2411.14   92.05 2408.72    98.5 2408.25
   105.8 2405.48   119.5 2403.57   122.9 2402.16   131.42397.324   133.2  2396.3
   136.6 2395.47   140.1 2395.41   145.8 2395.89   149.12397.441   153.8  2400.1
   160.7 2401.55   164.1 2401.69   177.8 2399.84   181.3 2400.48   191.5 2403.74
  215.422404.611     229 2404.98  239.762404.243   252.9 2404.14  276.782410.107
   300.6 2415.25   310.8  2416.7   324.4 2421.07   344.8 2422.94   366.9 2424.17
#Mann= 7 ,-1 , 0
       0     .12       0   92.05    .016       0   131.4    .045       0
   149.1     .12       0  215.42     .08       0  239.76    .016       0
  276.78     .12       0
#XS Ineff= 2 , 0
                          227.02         2405.29
Permanent Ineff=
       F       F
Bank Sta=131.4,149.1
XS Rating Curve= 0 ,0
Exp/Cntr=0.3,0.1

Type RM Length L Ch R = 1 ,1474.6  ,354.9,396.9,439.5
XS GIS Cut Line= 3
     2039327.132      347875.569     2039383.401      347700.218
     2039442.288      347507.856
#Sta/Elev= 30
       0 2423.42    12.6 2419.32   33.292413.692   53.942410.949  115.982405.252
   129.8 2404.27     147 2403.81   171.1 2404.07   181.5 2403.74   188.9  2404.3
   196.8 2401.67   207.2 2395.92   209.9 2394.88   215.8 2394.31   219.2 2394.61
   222.7 2396.13   229.5 2399.31  239.832400.559   250.1 2400.78     257 2402.36
   259.8 2402.56   274.1 2402.73  301.612412.144   315.3    2416  329.41 2418.67
   339.3  2419.9   359.9    2420  363.39 2420.41   377.1 2426.23   385.3 2428.78
#Mann= 11 ,-1 , 0
       0     .12       0   33.29     .06       0   53.94     .12       0
  115.98     .06       0     147     .12       0   207.2    .045       0
   222.7     .12       0  239.83    .016       0  301.61     .12       0
  329.41    .016       0  363.39     .12       0
Bank Sta=207.2,222.7
XS Rating Curve= 0 ,0
Exp/Cntr=0.5,0.3

Type RM Length L Ch R = 1 ,1077.7  ,315.1,302.1,289
XS GIS Cut Line= 3
     2039501.174       347995.96     2039660.822      347904.358
     2039891.134      347785.277
#Sta/Elev= 30
       0 2424.35    12.1  2419.3    21.5 2414.63    26.5 2413.57    81.5 2407.65
   134.7 2404.41   153.9    2404   172.8 2402.35   187.8 2402.32   202.2 2398.85
   213.7 2399.02   216.8  2398.5   221.7 2396.03   224.7 2394.67   232.1 2394.23
   235.8 2394.65   238.22396.039   243.2 2399.72   248.5 2401.09  252.122401.393
   272.8 2401.53   276.5 2402.03   283.8 2404.24  294.242405.365   324.5 2408.58
   350.7 2410.72   370.2 2414.59   401.9 2417.19   424.2 2425.21   443.3    2430
#Mann= 5 ,-1 , 0
       0     .12       0   221.7    .045       0   238.2     .12       0
  252.12    .016       0  294.24     .12       0
Bank Sta=221.7,238.2
XS Rating Curve= 0 ,0
Exp/Cntr=0.5,0.3

Type RM Length L Ch R = 1 ,775.7   ,448.4,445.5,440.5
XS GIS Cut Line= 3
     2039741.955      348252.443     2039874.122      348130.745
     2040066.485      347960.628
#Sta/Elev= 30
       0  2429.8    10.2 2427.32    22.8 2423.31    59.3 2415.74    99.4 2410.63
     114 2407.58   135.1 2404.83   173.7 2401.38   186.8    2401   194.7 2398.92
   205.9 2394.96   214.7 2393.97   227.2 2394.06   232.2 2395.25   241.1 2400.43
   245.8 2401.61  251.652401.531   280.9  2400.8  291.08    2404   300.7 2403.22
   341.7 2402.71   355.2 2402.84   370.1 2404.47   382.9  2407.9   387.6 2410.21
   394.5 2414.69   406.2 2418.57   415.5 2423.48   424.9 2430.92   436.5 2436.11
#Mann= 5 ,-1 , 0
       0     .12       0   205.9    .045       0   232.2     .12       0
  251.65    .016       0  291.08     .12       0
#XS Ineff= 2 , 0
                             250         2403.88
Permanent Ineff=
       F       F
Bank Sta=205.9,232.2
XS Rating Curve= 0 ,0
Exp/Cntr=0.5,0.3

Type RM Length L Ch R = 1 ,330.2   ,329.5,330.2,320.8
XS GIS Cut Line= 4
     2040185.858      348425.468     2040219.881      348353.496
     2040328.494      348243.574     2040386.072      347815.665
#Sta/Elev= 30
       0 2427.54    11.9    2424    42.5 2408.91    55.5 2404.78    69.6 2402.06
    85.8 2401.63    93.4 2398.62    98.1 2398.09   110.5  2397.2   124.5  2398.5
   136.5    2395   142.1 2393.52   157.2 2393.15   164.2 2393.58   167.7 2395.07
   171.2 2396.49   191.9 2399.52  269.82 2399.62  299.632398.526   306.4 2400.21
  332.152400.165  389.04 2398.34   458.7 2398.75   548.1 2400.72   561.3 2401.69
   571.3 2403.92   584.5 2408.52   604.4 2411.01   630.9 2417.01   665.9 2427.84
#Mann= 7 ,-1 , 0
       0     .12       0   136.5    .045       0   167.7     .12       0
  269.82    .016       0  299.63     .12       0  332.15     .06       0
  389.04     .12       0
#XS Ineff= 2 , 0
                          316.17            2410
Permanent Ineff=
       F       F
Bank Sta=136.5,167.7
XS Rating Curve= 0 ,0
Exp/Cntr=0.3,0.1
LCMann Table=0

Chan Stop Cuts=-1
Use User Specified Reach Order=0
Composite Channel Slope=5